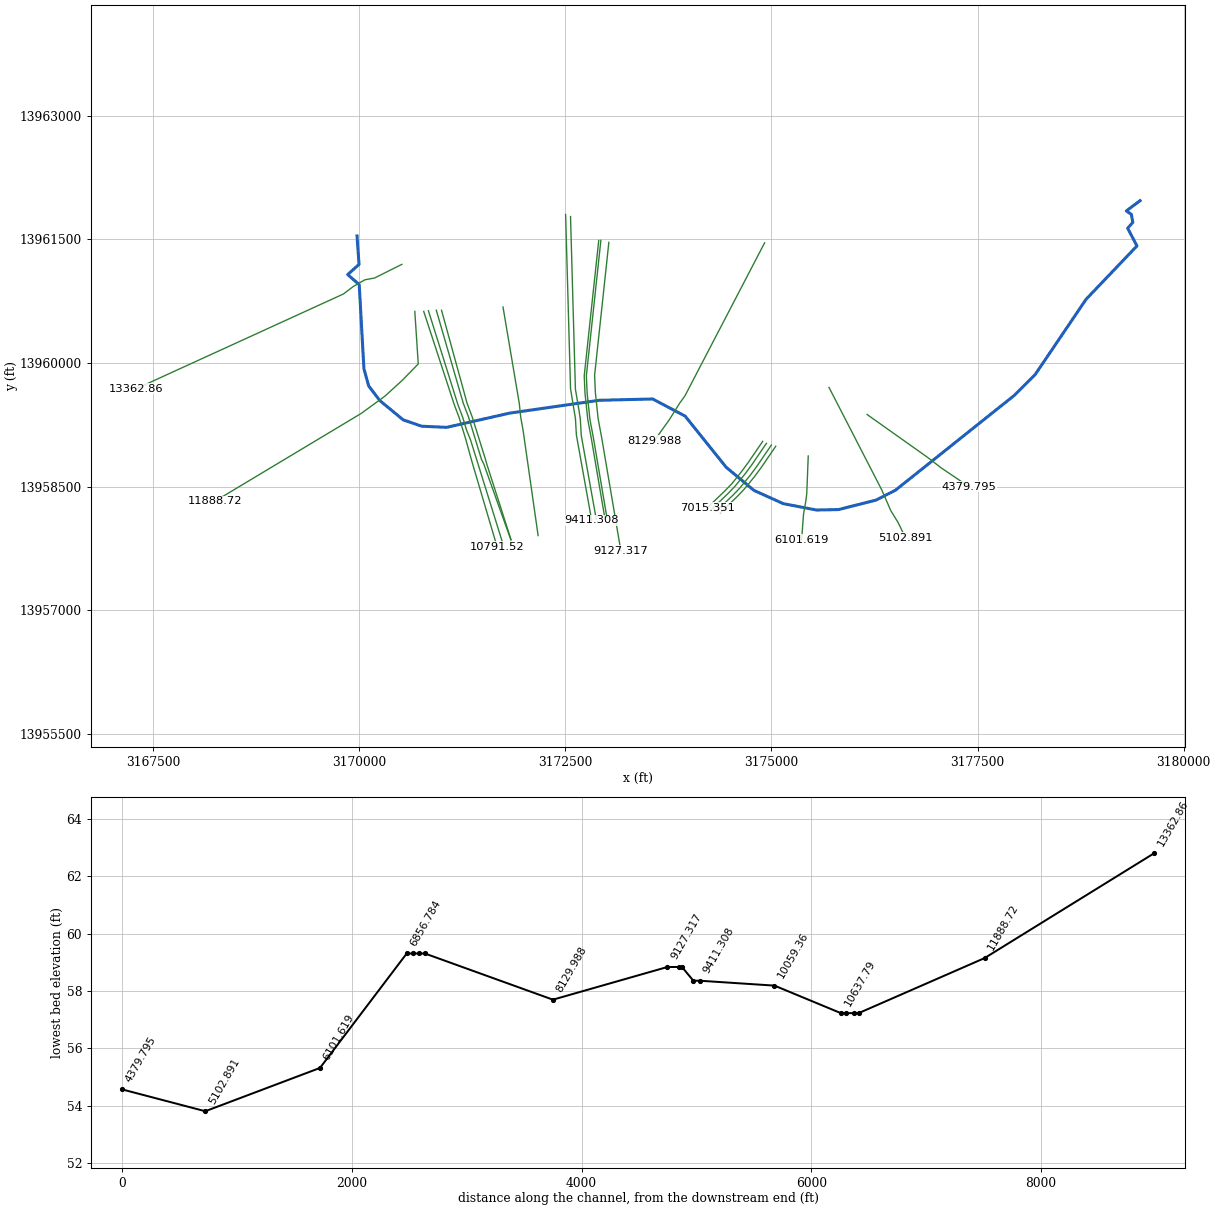
--- G103-80-031B.prj (project) ---

Proj Title=G103-80-03.1B
Current Plan=p06
Default Exp/Contr=.3,.1
English Units
Geom File=g03
Flow File=f04
Flow File=f01
Plan File=p04
Plan File=p06
Y Axis Title=Elevation
X Axis Title(PF)=Main Channel Distance
X Axis Title(XS)=Station
BEGIN DESCRIPTION:
San Jacinto Watershed
Taylor Gully
HCFCD unit G 103-80-03.1B
(Flood Hazard, Floodway)Model
10, 2, 1, 0.2% Event
Filename  G10380031.prj
Prepared by:  FTN Associates Ltd.   DATE:  May 2003
Reviewed by:     DATE:
STATUS (Final RAS)
415 Taylor Gully:  V3 lidar, surveys, FIS Mannings, FIS Flow, structures, White Oak/Taylor stream centerline changed.
Starting condition is normal depth, channel slope= 0.000677 computed from RS 2306.81 (415s8u) @ 42.32 ft and RS 902.652 (415v9) @ 41.37 ft.
END DESCRIPTION:
DSS Export Rating Curves= 0
DSS Export Rating Curve Sorted= 0
DSS Export Volume Flow Curves= 0
DXF OffsetX= 0
DXF OffsetY= 0
DXF ScaleX= 1
DXF ScaleY= 10

--- G103-80-031B.p06 (plan) ---

Plan Title=Floodway
Version=Version 3.0.1  Mar 2001
Short Identifier=Floodway0607
Geom File=g03
Flow File=f01
Subcritical Flow
K Sum by GR= 0
Std Step Tol= 0.01
Critical Tol= 0.01
Num of Std Step Trials= 20
Max Error Tol= 0.3
Flow Tol Ratio= 0.001
Split Flow NTrial= 30
Split Flow Tol= 0.02
Split Flow Ratio= 0.02
Log Output Level= 0
Friction Slope Method= 1
Unsteady Friction Slope Method= 2
Parabolic Critical Depth
Global Vel Dist= 0 , 0 , 0
Global Log Level= 0
CheckData=True
Encroach Param=-1 ,0,0, 2
Encroach River=G103-80-031B
Encroach Reach=G10380031B_0001
Encroach Node=13362.86
       1  542.42  602.23
Encroach Node=11888.72
       1  594.34  694.12
Encroach Node=10791.52
       1   548.5  642.44
Encroach Node=10749.18
       1  540.91  634.85
Encroach Node=10714.80
       1  540.91  634.85
Encroach Node=10680.41
       1  519.69  613.63
Encroach Node=10637.79
       1  525.13  619.07
Encroach Node=10059.36
       1  488.61  593.05
Encroach Node=9411.308
       1  480.08  593.31
Encroach Node=9352.978
       1  471.34  584.57
Encroach Node=9303.294
       1   461.5  584.57
Encroach Node=9253.604
       1   461.5   572.1
Encroach Node=9240.554
       1     450     574
Encroach Node=9227.494
       1  459.28  569.88
Encroach Node=9127.317
       1  450.41  561.01
Encroach Node=8129.988
       1   569.6  678.42
Encroach Node=7015.351
       1  475.12  600.35
Encroach Node=6967.086
       1  477.18  602.41
Encroach Node=6937.364
       1  477.18  617.15
Encroach Node=6907.639
       1  491.92  617.15
Encroach Node=6856.784
       1  510.88  636.11
Encroach Node=6101.619
       1  591.35  687.23
Encroach Node=5102.891
       1  570.88  657.42
Encroach Node=4379.795
       1  442.82  543.93
Encroach Node=4326.764
       1  448.44  549.55
Encroach Node=4297.624
       1  448.44  550.66
Encroach Node=4268.481
       1  449.55  550.66
Encroach Node=4211.277
       1  447.31  548.42
Encroach Node=3502.953
       1  508.19  600.81
Encroach Node=3454.339
       1  500.91  593.53
Encroach Node=3440.990
       1     495     603
Encroach Node=3427.639
       1  500.91  593.53
Encroach Node=3385.195
       1  490.05  582.67
Encroach Node=3287.034
       1  514.92  608.91
Encroach Node=2911.472
       1  429.39  524.16
Encroach Node=2854.677
       1  425.18  519.95
Encroach Node=2840
       1  425.18  519.95
Encroach Node=2808.660
       1  425.18  519.95
Encroach Node=2724.167
       1  367.32  462.09
Encroach Node=2306.809
       1  398.24  495.17
Encroach Node=2257.737
       1  379.69  476.62
Encroach Node=2228.369
       1  379.69   505.8
Encroach Node=2199.002
       1  408.87   505.8
Encroach Node=2155.758
       1  426.65  523.58
Encroach Node=902.652
       1 1055.86 1142.28
Encroach Node=83.251
       1 1083.69    1211
Computation Interval=1HOUR
Output Interval=1HOUR
Run HTab= 0
Run UNet= 0
Run PostProcess= 0
UNET Theta= 1
UNET ZTol= 0.02
UNET ZSATol= 0.1
UNET MxIter= 20
UNET MaxInSteps= 20
UNET DtIC= 0
UNET DtMin= 0
UNET MaxCRTS= 20
UNET WFStab= 2
UNET SFStab= 1
UNET WFX= 1
UNET SFX= 1
UNET Convert EG Bridges=-1
UNET Use Existing IB Tables=-1
Instantaneous Interval=1HOUR
Write IC File= 0
Write Velocity= 0
Write Detailed= 0

--- G103-80-031B.p04 (plan) ---

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Plan Title=FEMA Effective June 2007
Short Identifier=FEMAeff0607
Geom File=g03
Flow File=f04
Encroach Param=-1 ,0,0, 0
IC Time=0

--- G103-80-031B.f01 (steady flow) ---

Flow Title=Floodway
Version=Version 3.0.1  Mar 2001
Number of Profiles= 2
Profile Names=1PCT_100yr, 1PCTFloodway_100yrFW
River Rch & RM=G103-80-031B,G10380031B_0001    ,13362.86
    1497    1497
River Rch & RM=G103-80-031B,G10380031B_0001    ,11888.72
    1622    1622
River Rch & RM=G103-80-031B,G10380031B_0001    ,10791.52
    1791    1791
River Rch & RM=G103-80-031B,G10380031B_0001    ,10059.36
    1855    1855
River Rch & RM=G103-80-031B,G10380031B_0001    ,9411.308
    1884    1884
River Rch & RM=G103-80-031B,G10380031B_0001    ,9127.317
    1989    1989
River Rch & RM=G103-80-031B,G10380031B_0001    ,8129.988
    2113    2113
River Rch & RM=G103-80-031B,G10380031B_0001    ,7015.351
    2131    2131
River Rch & RM=G103-80-031B,G10380031B_0001    ,6856.784
    2220    2220
River Rch & RM=G103-80-031B,G10380031B_0001    ,6101.619
    2344    2344
River Rch & RM=G103-80-031B,G10380031B_0001    ,5102.891
    2460    2460
River Rch & RM=G103-80-031B,G10380031B_0001    ,4211.277
    2556    2556
River Rch & RM=G103-80-031B,G10380031B_0001    ,3502.953
    2667    2667
River Rch & RM=G103-80-031B,G10380031B_0001    ,2724.167
    2750    2750
River Rch & RM=G103-80-031B,G10380031B_0001    ,2155.758
    2944    2944
River Rch & RM=G103-80-031B,G10380031B_0001    ,902.652
    3078    3078
Boundary for River Rch & Prof#=G103-80-031B,G10380031B_0001    , 1
Up Type= 0
Dn Type= 3
Dn Slope=.000677
Boundary for River Rch & Prof#=G103-80-031B,G10380031B_0001    , 2
Up Type= 0
Dn Type= 3
Dn Slope=.000677
DSS Import GetInterval= 0
DSS Import GetPeak= 0
DSS Import FillOption= 0

--- G103-80-031B.f04 (steady flow) ---

Flow Title=FEMA Effective June 2007
Version=Version 3.0.1  Mar 2001
Number of Profiles= 4
Profile Names=10PCT_10yr, 2PCT_50yr, 1PCT_100yr, 0.2PCT_500yr
River Rch & RM=G103-80-031B,G10380031B_0001    ,13362.86
     945    1305    1497    1969
River Rch & RM=G103-80-031B,G10380031B_0001    ,11888.72
    1021    1417    1622    2131
River Rch & RM=G103-80-031B,G10380031B_0001    ,10791.52
    1124    1569    1791    2350
River Rch & RM=G103-80-031B,G10380031B_0001    ,10059.36
    1163    1627    1855    2433
River Rch & RM=G103-80-031B,G10380031B_0001    ,9411.308
    1181    1653    1884    2470
River Rch & RM=G103-80-031B,G10380031B_0001    ,9127.317
    1244    1748    1989    2606
River Rch & RM=G103-80-031B,G10380031B_0001    ,8129.988
    1319    1860    2113    2766
River Rch & RM=G103-80-031B,G10380031B_0001    ,7015.351
    1330    1876    2131    2790
River Rch & RM=G103-80-031B,G10380031B_0001    ,6856.784
    1384    1957    2220    2905
River Rch & RM=G103-80-031B,G10380031B_0001    ,6101.619
    1458    2069    2344    3064
River Rch & RM=G103-80-031B,G10380031B_0001    ,5102.891
    1528    2175    2460    3214
River Rch & RM=G103-80-031B,G10380031B_0001    ,4211.277
    1586    2263    2556    3339
River Rch & RM=G103-80-031B,G10380031B_0001    ,3502.953
    1652    2364    2667    3481
River Rch & RM=G103-80-031B,G10380031B_0001    ,2724.167
    1702    2440    2750    3588
River Rch & RM=G103-80-031B,G10380031B_0001    ,2155.758
    1818    2617    2944    3837
River Rch & RM=G103-80-031B,G10380031B_0001    ,902.652
    1897    2739    3078    4010
Boundary for River Rch & Prof#=G103-80-031B,G10380031B_0001    , 1
Up Type= 0
Dn Type= 3
Dn Slope=.000677
Boundary for River Rch & Prof#=G103-80-031B,G10380031B_0001    , 2
Up Type= 0
Dn Type= 3
Dn Slope=.000677
Boundary for River Rch & Prof#=G103-80-031B,G10380031B_0001    , 3
Up Type= 0
Dn Type= 3
Dn Slope=.000677
Boundary for River Rch & Prof#=G103-80-031B,G10380031B_0001    , 4
Up Type= 0
Dn Type= 3
Dn Slope=.000677
DSS Import GetInterval= 0
DSS Import GetPeak= 0
DSS Import FillOption= 0

--- G103-80-031B.g03 (geometry) ---

Geom Title=G103-80-031b June 2007
Version=Version 3.0.1  Mar 2001

River Reach=G103-80-031B   ,G10380031B_0001
Reach XY= 30
     3169973.956    13961538.579     3169998.768    13961194.355
     3169860.908    13961070.856     3170000.901    13960948.865
     3170057.815    13959928.913     3170115.441    13959720.441
     3170248.639    13959544.346     3170533.935    13959308.854
     3170758.381    13959231.443     3171061.237    13959217.748
     3171826.491    13959390.458     3172909.013    13959545.822
     3173559.564    13959561.996     3173953.069    13959354.637
     3174451.842    13958733.517     3174788.043    13958453.328
      3175143.39    13958292.664     3175547.203    13958214.854
     3175814.833    13958220.611     3176268.174    13958334.974
     3176504.537    13958455.131      3177944.45     13959604.01
     3178199.839    13959858.791     3178817.383    13960771.945
     3179433.948    13961418.203     3179321.045    13961633.152
     3179383.807    13961703.591     3179365.383     13961801.65
     3179304.412    13961842.671     3179471.964    13961967.135

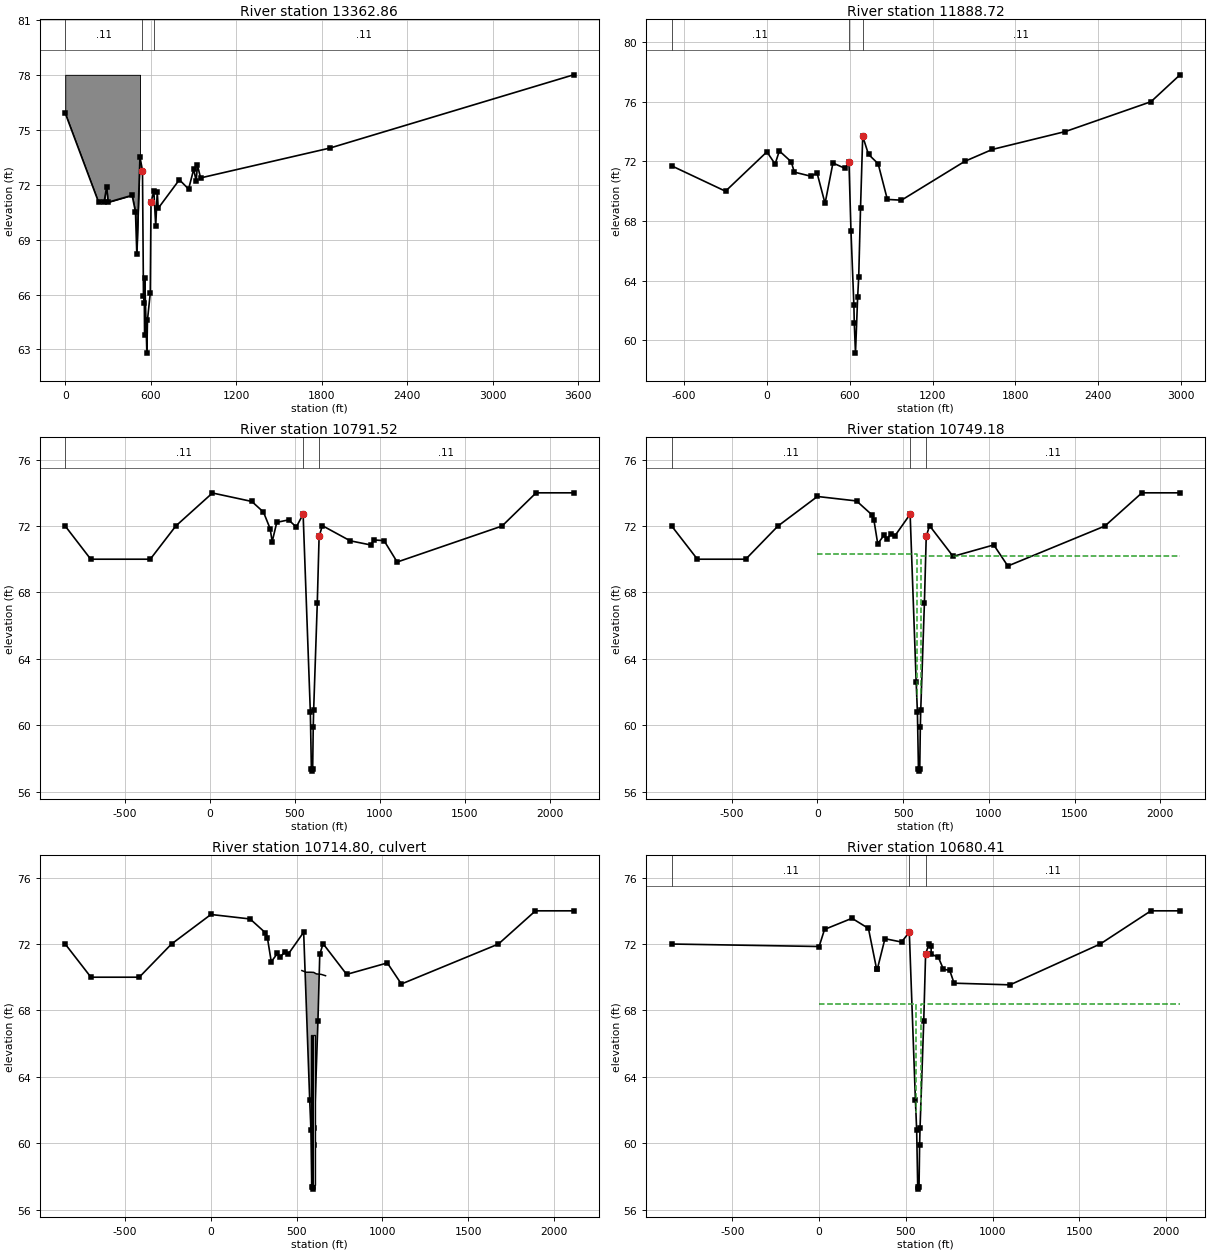
Type RM Length L Ch R = 1 ,13362.86,1458.87,1474.14,1488.14
BEGIN DESCRIPTION:
415v2
Bank Station offset =      4427
LOB block at watershed edge
END DESCRIPTION:
XS GIS Cut Line= 6
     3170517.932     13961194.57     3170188.125    13961029.667
     3170068.399    13961006.909     3169926.356     13960924.48
     3169809.816    13960835.662 3167293.627852613959685.4020202
#Sta/Elev= 30
       0   75.91  233.83   71.05  273.08   71.07  290.92   71.88  300.65   71.04
   469.7   71.42  493.27   70.51  502.59   68.19  524.68   73.52  542.42   72.77
  549.24   65.94  556.18   65.52  558.01   63.79  558.32   66.93  573.15    62.8
  577.46   64.61     597   66.07  602.23   71.04  622.18   71.65  635.36   69.74
   646.1   71.62  652.75   70.71  801.36   72.27  866.04   71.76  902.19   72.85
  919.28   72.18  928.11   73.06  950.44   72.37    1858      74    3568      78
#Mann= 3 ,-1 , 0
       0     .11       0  542.42     .04       0  622.18     .11       0
#Block Obstruct= 2 , 0
       0     525      78               0
Bank Sta=542.42,602.23
XS Rating Curve= 0
Exp/Cntr=.3,.1

Type RM Length L Ch R = 1 ,11888.72,1009.66,1097.2,1166.2
BEGIN DESCRIPTION:
415v3
Bank Station offset =      4358
Block left overbank to keep flow in section.
END DESCRIPTION:
XS GIS Cut Line= 6
        3170675.       13960625. 3170716.788349713959986.8913835
     3170522.782     13959788.04     3170312.192     13959595.65
     3170023.221     13959385.48     3168246.072     13958319.19
#Sta/Elev= 30
    -690    71.7    -300      70       0   72.64   59.41   71.82   90.11    72.7
  176.55   71.97  198.42   71.28  316.36   71.01   364.1    71.2  421.25   69.18
  478.41   71.89   566.7   71.53  594.34   71.96  609.07   67.34  630.19   62.35
  633.02   61.16   641.8   59.15  657.34   62.88  665.15   64.25  678.34   68.88
  694.12   73.68  736.12   72.47     806   71.84  872.59   69.45  975.12    69.4
    1433      72    1633    72.8    2163      74    2783      76    2993    77.8
#Mann= 3 ,-1 , 0
    -690     .11       0  594.34     .04       0  694.12     .11       0
#Block Obstruct= 2 , 0
       0    -685      77               0
Bank Sta=594.34,694.12
XS Rating Curve= 0
Exp/Cntr=.3,.1

Type RM Length L Ch R = 1 ,10791.52,42.34,42.34,42.44
BEGIN DESCRIPTION:
415s1u:  XS 4/4
Bank Station offset =      4399
ROB Extended
END DESCRIPTION:
XS GIS Cut Line= 6
 3170783.3483036 13960623.448123     3171153.275    13959494.235
     3171213.077      13959335.1      3171293.95    13959070.221
     3171361.852    13958822.865  3171672.36749613957771.4797702
#Sta/Elev= 30
    -850      72    -700      70    -350      70    -200      72   15.55   73.99
   246.9   73.48  315.41   72.84  354.59   71.84  366.65   71.06  393.63   72.22
  463.19   72.37  508.26   71.94   548.5   72.71  590.96   60.78  597.01   57.36
  600.71   57.23  604.59   57.37   607.9   59.86  610.41   60.92  631.67   67.34
  642.44   71.38  661.77   72.02  824.81   71.11   945.4   70.86  965.52   71.16
 1024.13   71.12 1101.41   69.83    1718      72    1918      74    2138      74
#Mann= 3 ,-1 , 0
    -850     .11       0   548.5     .04       0  642.44     .11       0
#Block Obstruct= 2 , 0
       0    -845      77    2135       0      77
Bank Sta=548.5,642.44
XS Rating Curve= 0
Exp/Cntr=.5,.3

Type RM Length L Ch R = 1 ,10749.18,68.75,68.77,68.95
BEGIN DESCRIPTION:
copy of 415s1u, XS 3/4, adjust elevations as needed
Bank Station offset =      4407
ROB Extended
END DESCRIPTION:
XS GIS Cut Line= 6
 3170840.0169966 13960632.876901     3171196.275    13959498.235
     3171256.077      13959339.1      3171303.93    13959180.867
     3171349.821    13959068.834 3171742.486821213957809.2951693
#Sta/Elev= 30
    -850      72    -700      70    -418      70    -230      72       0   73.78
  228.41   73.51  317.42   72.68  329.48   72.37   351.9   70.93  388.25   71.44
   404.3   71.21  429.94   71.52  450.89   71.39  540.91   72.71  576.09   62.61
  583.37   60.78  589.42   57.36  593.12   57.23     597   57.37  600.31   59.86
  602.82   60.92  624.08   67.34  634.85   71.38  654.18   72.02   791.5   70.17
 1028.84   70.86  1110.7   69.59    1677      72    1893      74    2115      74
#Mann= 3 ,-1 , 0
    -850     .11       0  540.91     .04       0  634.85     .11       0
#XS Ineff= 2 , 0
       0     580    70.3     606       0    70.2
Permanent Ineff=
       F       F
#Block Obstruct= 2 , 0
       0    -845      77    2110       0      77
Bank Sta=540.91,634.85
XS Rating Curve= 0
Exp/Cntr=.5,.3

Type RM Length L Ch R = 2 ,10714.80,,,
BEGIN DESCRIPTION:
415s1: Rustling Elms Rd. "2- 10' x 9' conc. box culverts"
END DESCRIPTION:
Bridge Culvert--1,0,-1,-1, 0
Deck Dist Width WeirC Skew NumUp NumDn MinLoCord MaxHiCord MaxSubmerge Is_Ogee
19.1,30.45,2.6,0, 7, 7, 70.17, , .95, 0, 0,0,,
   530.4   555.7  580.62  599.52  614.79  643.26  668.49
    70.4    70.3    70.3   70.29    70.2   70.17   70.09
       0       0       0       0       0       0       0
   509.4   534.7  559.62  578.52  593.79  622.26  647.49
    70.4    70.3    70.3   70.29    70.2   70.17   70.09
       0       0       0       0       0       0       0
BR Coef=-1 , 0 , 0 ,, 0 ,,,.8,-1,,0,
WSPro=,,,, 1 ,,,, 0 ,,,, 0 ,,,,-1 ,-1 ,-1 , 0 , 0 , 0 , 0 , 0
Multiple Barrel Culv=2,9,10,43.46,.012,.4,1,8,1,57.5,57.55, 2,415s1       , 0 ,12.66
  586.83  564.83  599.18  578.18
Culvert Bottom n=.012
BC Design=,, 0 ,, 0 ,,,,,,

Type RM Length L Ch R = 1 ,10680.41,42.19,42.62,42.74
BEGIN DESCRIPTION:
copy of 415s1u, XS 2/4, adjust elevations as needed
Bank Station offset =      4428
ROB Extended.
LOB block at end of section to keep water in section.
END DESCRIPTION:
XS GIS Cut Line= 6
 3170935.696757513960638.2766346     3171262.688    13959510.723
     3171326.077      13959345.1     3171483.633    13958829.218
      3171511.64    13958773.203 3171839.511398513957855.3140323
#Sta/Elev= 30
    -850      72       0   71.85   31.11   72.88   189.4   73.55  284.19   72.94
  330.68   70.52  335.77    70.5  379.29   72.32  474.83   72.12  519.69   72.71
  554.87   62.61  562.15   60.78   568.2   57.36   571.9   57.23  575.78   57.37
  579.09   59.86   581.6   60.92  602.86   67.34  613.63   71.38  632.96   72.02
  645.64   71.87  645.73    71.4  687.68   71.19  716.29   70.48  752.75   70.41
  777.79   69.64 1100.34   69.54    1620      72 1912.45      74    2080      74
#Mann= 3 ,-1 , 0
    -850     .11       0  519.69     .04       0  613.63     .11       0
#XS Ineff= 2 , 0
       0     558    68.4     585       0    68.4
Permanent Ineff=
       F       F
#Block Obstruct= 2 , 0
       0    -845      77    2075       0      77
Bank Sta=519.69,613.63
XS Rating Curve= 0
Exp/Cntr=.5,.3

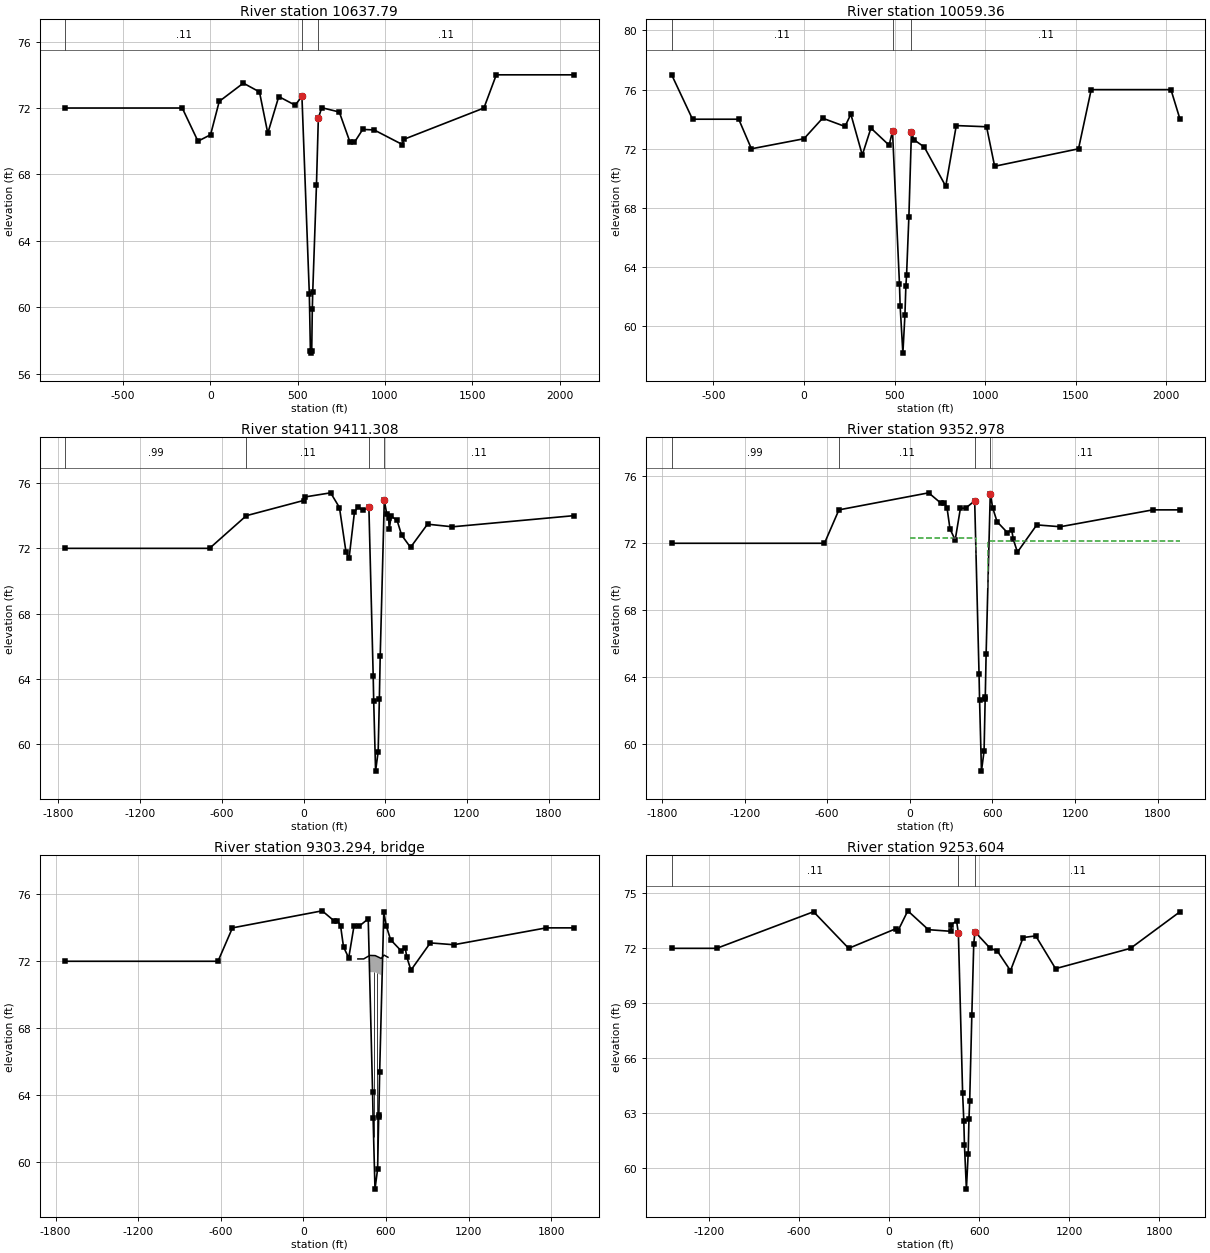
Type RM Length L Ch R = 1 ,10637.79,594.63,578.42,565.69
BEGIN DESCRIPTION:
copy of 415s1u, XS 1/4, adjust elevations as needed
Bank Station offset =      4423
ROB Extended
LOB block at end of section to keep water in section.
END DESCRIPTION:
XS GIS Cut Line= 6
 3170999.2964225 13960637.832366     3171309.275    13959509.235
     3171369.077      13959350.1     3171530.311    13958835.441
     3171545.871    13958779.427 3171842.580842613957853.5519502
#Sta/Elev= 30
    -830      72    -160      72     -70      70    2.12   70.39   51.86    72.4
  189.79    73.5   282.1   72.97   329.7   70.48  392.53   72.69  486.68   72.17
  525.13   72.71  567.59   60.78  573.64   57.36  577.34   57.23  581.22   57.37
  584.53   59.86  587.04   60.92   608.3   67.34  619.07   71.38   638.4   72.02
  739.04   71.76   799.1   69.98  825.43   69.93  873.06   70.71  938.36   70.68
 1099.93    69.8 1107.87   70.11    1567      72 1637.86      74    2080      74
#Mann= 3 ,-1 , 0
    -830     .11       0  525.13     .04       0  619.07     .11       0
#Block Obstruct= 2 , 0
       0    -825      77    2075       0      77
Bank Sta=525.13,619.07
XS Rating Curve= 0
Exp/Cntr=.3,.1

Type RM Length L Ch R = 1 ,10059.36,642.94,648.06,651.98
BEGIN DESCRIPTION:
415v4
Bank Station offset =      4454
Blocked low area in ROB.  Area determined unavailable to flow or storage.
END DESCRIPTION:
XS GIS Cut Line= 6
 3171744.744602213960677.6065844     3171942.728    13959504.861
     3171952.498    13959409.116     3171959.337     13959342.68
     3171987.517    13959186.624 3172170.519292213957905.5749385
#Sta/Elev= 30
    -730      77    -615      74    -360      74    -290      72       0   72.68
  102.94   74.07  226.34   73.51  258.75   74.34  321.86   71.58  369.53    73.4
  469.96   72.24  488.61   73.19  526.99   62.87  530.73   61.37  545.81   58.19
  557.02   60.74  562.41   62.75   566.1   63.45   578.9   67.39  593.05   73.14
  605.97   72.62   663.9   72.12  782.34   69.47  840.42   73.57 1007.58   73.49
 1052.13   70.82    1515      72    1585      76    2025      76    2075      74
#Mann= 3 ,-1 , 0
    -730     .11       0  488.61     .04       0  593.05     .11       0
#Block Obstruct= 2 , 0
       0                    2025       0      77
Bank Sta=488.61,593.05
XS Rating Curve= 0
Exp/Cntr=.3,.1

Type RM Length L Ch R = 1 ,9411.308,57.8,58.33,58.74
BEGIN DESCRIPTION:
copy of 415s3u, XS 4/4, adjust elevations as needed
Bank Station offset =      4471
END DESCRIPTION:
XS GIS Cut Line= 6
 3172504.105465713961799.3411695     3172563.881    13959686.335
     3172606.888    13959422.527     3172622.943    13959327.836
       3172634.9    13959124.567 3172820.400874513958088.8532454
#Sta/Elev= 30
   -1750      72    -690      72    -420      74       0   74.93    12.6   75.15
  199.25    75.4  263.96    74.5  312.31   71.76  334.75   71.41  374.05   74.21
   399.6   74.54  435.66   74.33  480.08   74.54  511.76   64.18  515.54   62.64
   529.3   58.36   548.3   59.56  556.97   62.77  563.29    65.4  593.31   74.95
  610.75   74.13  625.09   73.86  629.45   73.16  643.34   73.97  686.95   73.72
  720.63   72.81  785.89   72.06  910.73   73.48 1093.58   73.32    1983      74
#Mann= 4 ,-1 , 0
   -1750     .99       0    -420     .11       0  480.08     .04       0
  593.31     .11       0
#Block Obstruct= 2 , 0
       0   -1745      77    1980       0      77
Bank Sta=480.08,593.31
XS Rating Curve= 0
Exp/Cntr=.5,.3

Type RM Length L Ch R = 1 ,9352.978,105.41,99.37,94.79
BEGIN DESCRIPTION:
415s3u:  XS 3/4, and XS 4/4 for 415s2u
Bank Station offset =      4479
END DESCRIPTION:
XS GIS Cut Line= 6
 3172563.671026113961774.3491675     3172622.881    13959681.335
     3172667.897    13959414.941     3172681.943    13959322.836
       3172693.9    13959119.567 3172875.873129613958103.5498315
#Sta/Elev= 30
   -1730      72    -620      72    -515      74  136.99   75.02  224.79   74.41
  246.82   74.44  270.21   74.14  291.89   72.86  329.75    72.2  367.87    74.1
  405.34    74.1  471.34   74.54  503.02   64.18   506.8   62.64  520.56   58.36
  539.56   59.56  547.45   62.65  548.23   62.77  554.55    65.4  584.57   74.95
  602.01   74.13  634.03   73.29  708.66   72.64  739.63   72.82  752.33   72.23
  781.82   71.47  922.34    73.1 1093.59   72.99    1765      74    1963      74
#Mann= 4 ,-1 , 0
   -1730     .99       0    -515     .11       0  471.34     .04       0
  584.57     .11       0
#XS Ineff= 2 , 0
       0   481.2    72.3   566.9       0   72.15
Permanent Ineff=
       F       F
#Block Obstruct= 2 , 0
       0   -1725      77    1960       0      77
Bank Sta=471.34,584.57
XS Rating Curve= 0
Exp/Cntr=.5,.3

Type RM Length L Ch R = 3 ,9303.294,,,
BEGIN DESCRIPTION:
415s3: West Lake Houston Pkwy "conc. bridge"
END DESCRIPTION:
Bridge Culvert--1,0,-1,-1, 0
Deck Dist Width WeirC Skew NumUp NumDn MinLoCord MaxHiCord MaxSubmerge Is_Ogee
35.7,27.9,2.6,0, 7, 7, 72.14, , .95, 0, 0,0,,
   396.2  438.44   482.2  522.14  565.74  586.22  614.77
   72.14   72.14   72.35   72.34   72.17   72.37   72.24
       0       0   71.35   71.34   71.17       0       0
   390.2  432.44   476.2  516.14  559.74  580.22  608.77
   72.14   72.14   72.35   72.34   72.17   72.37   72.24
       0       0   71.35   71.34   71.17       0       0
Pier Skew, UpSta & Num, DnSta & Num=  ,510.5, 4 ,504.5, 4 , 3 , 3 , 0 ,0,
    1.35    1.35     1.5     1.5
      58   69.85   69.85   71.35
    1.35    1.35     1.5     1.5
      58   69.85   69.85   71.35
Pier Skew, UpSta & Num, DnSta & Num=  ,537.87, 4 ,531.87, 4 , 3 , 3 , 0 ,0,
    1.35    1.35     1.5     1.5
      58   69.78   69.78   71.28
    1.35    1.35     1.5     1.5
      58   69.78   69.78   71.28
BR Coef=-1 , 0 , 0 ,, 0 ,,,.8,-1,,0,
WSPro=,,,, 1 ,,,, 0 ,,,, 0 ,,,,-1 ,-1 ,-1 , 0 , 0 , 0 , 0 , 0
BC Design=,, 0 ,, 0 ,,,,,,

Type RM Length L Ch R = 1 ,9253.604,26.07,26.11,26.09
BEGIN DESCRIPTION:
415s2u:  XS 3/4; and XS 2/4 for 415s3u
Bank Station offset =      4485
Block ROB at end to keep water in XS
END DESCRIPTION:
XS GIS Cut Line= 6
 3172905.769563513961484.3980017     3172729.771    13959841.772
      3172739.18    13959631.538     3172772.816    13959313.271
     3172815.862    13959083.696  3172978.41194713958124.6485939
#Sta/Elev= 30
   -1450      72   -1150      72    -504      74    -270      72   43.78   73.07
    58.8   72.96  124.33   74.05   261.4   73.02  412.63   72.93  413.79   73.29
  449.33    73.5   461.5   72.82  489.79   64.08  497.68   62.56  501.99   61.24
  514.95   58.84  526.77   60.77  531.96   62.66  536.92   63.67  551.09   68.34
  563.87   72.24   572.1    72.9  673.76      72  720.45   71.86  808.79   70.78
   893.5   72.59  977.18   72.68 1109.38   70.89    1609      72    1939      74
#Mann= 3 ,-1 , 0
   -1450     .11       0   461.5     .04       0   572.1     .11       0
#XS Ineff= 2 , 0
       0     453   72.14   573.5       0   72.14
Permanent Ineff=
       F       F
#Block Obstruct= 2 , 0
       0   -1445      77    1935       0      77
Bank Sta=461.5,572.1
XS Rating Curve= 0
Exp/Cntr=.5,.3

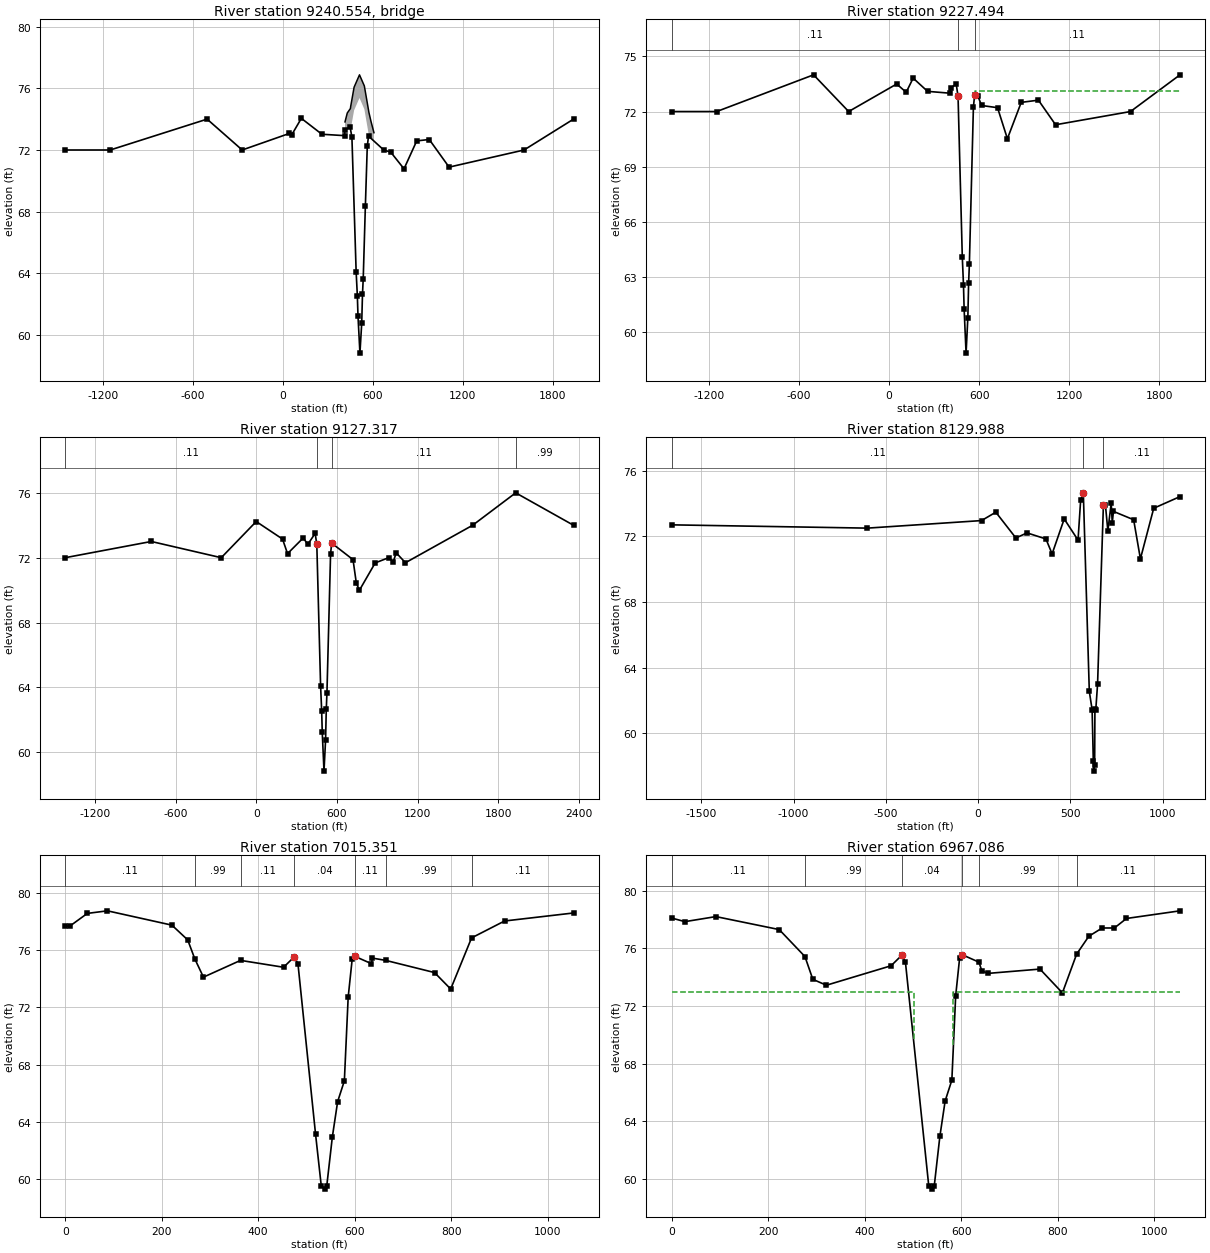
Type RM Length L Ch R = 3 ,9240.554,,,
BEGIN DESCRIPTION:
415s2: FOOTBRIDGE Walkway east of West Lake Houston Pkwy  "meta l& wood walk bridge"
LC = HC - 1.5'
END DESCRIPTION:
Bridge Culvert--1,0,-1,-1, 0
Deck Dist Width WeirC Skew NumUp NumDn MinLoCord MaxHiCord MaxSubmerge Is_Ogee
10,6,2.6,0, 11, 11, , , .95, 0, 0,0,,
  415.39  430.62  451.69  452.71  476.06  512.04  544.36   573.5  574.48  588.49
  608.43
   73.82    74.4   74.69   74.79   76.07   76.87   76.15   74.51   74.45   73.86
   73.12
       0       0       0   73.29   74.57   75.37   74.65   73.01       0       0
       0
  413.39  428.62  449.69  450.71  474.06  510.04  542.36   571.5  572.48  586.49
  606.43
   73.82    74.4   74.69   74.79   76.07   76.87   76.15   74.51   74.45   73.86
   73.12
       0       0       0   73.29   74.57   75.37   74.65   73.01       0       0
       0
BR Coef=-1 , 0 , 0 ,, 0 ,,,.8,0,,0,
WSPro=,,,, 1 ,,,, 0 ,,,, 0 ,,,,-1 ,-1 ,-1 , 0 , 0 , 0 , 0 , 0
BC Design=,, 0 ,, 0 ,,,,,,

Type RM Length L Ch R = 1 ,9227.494,99.99,100.18,100.12
BEGIN DESCRIPTION:
copy of 415s2u, XS 2/4; and XS 1/4 for 415s3u
Bank Station offset =      4487
Extended LOB and ROB and Blocked at watershed edges
END DESCRIPTION:
XS GIS Cut Line= 6
 3172931.769563513961486.3980017     3172755.771    13959843.772
      3172765.18    13959633.538     3172798.816    13959315.271
     3172841.862    13959085.696  3173004.41194713958126.6485939
#Sta/Elev= 30
   -1450      72   -1150      72    -504      74    -270      72   50.04    73.5
  113.54   73.05  159.85   73.82  256.06    73.1  403.96      73  411.57   73.29
  447.11    73.5  459.28   72.82  487.57   64.08  495.46   62.56  499.77   61.24
  512.73   58.84  524.55   60.77  529.74   62.66   534.7   63.67  561.65   72.24
  569.88    72.9  591.77   72.84  615.98   72.33  722.47   72.21  788.23   70.52
  880.53    72.5  995.04   72.62 1109.38   71.28    1609      72    1939      74
#Mann= 3 ,-1 , 0
   -1450     .11       0  459.28     .04       0  569.88     .11       0
#XS Ineff= 2 , 0
       0     448   73.12     572       0   73.12
Permanent Ineff=
       F       F
#Block Obstruct= 2 , 0
       0   -1445      77    1935       0      77
Bank Sta=459.28,569.88
XS Rating Curve= 0
Exp/Cntr=.5,.3

Type RM Length L Ch R = 1 ,9127.317,1049.09,997.33,944.84
BEGIN DESCRIPTION:
copy of 415s2u, XS 1/4
Bank Station offset =      4496
Extended LOB and ROB and Blocked at watershed edges
END DESCRIPTION:
XS GIS Cut Line= 6
 3173028.573517313961461.5687327     3172855.771    13959848.772
      3172865.18    13959638.538     3172898.816    13959320.271
     3172941.862    13959090.696 3173174.597210213957717.5543669
#Sta/Elev= 30
   -1420      72    -780      73    -260      72       0   74.23  195.55   73.15
  232.87   72.25  349.63   73.22  383.28   72.82  438.24    73.5  450.41   72.82
   478.7   64.08  486.59   62.56   490.9   61.24  503.86   58.84  515.68   60.77
  520.87   62.66  525.83   63.67  552.78   72.24  561.01    72.9  719.63   71.88
  744.16   70.44  767.09   69.99  884.58   71.68  988.17   72.01    1018   71.73
 1040.75    72.3 1109.38   71.69    1609      74    1929      76    2359      74
#Mann= 4 ,-1 , 0
   -1420     .11       0  450.41     .04       0  561.01     .11       0
    1929     .99       0
#Block Obstruct= 2 , 0
       0   -1415      77    2355       0      77
Bank Sta=450.41,561.01
XS Rating Curve= 0
Exp/Cntr=.3,.1

Type RM Length L Ch R = 1 ,8129.988,1122.99,1114.64,1105.83
BEGIN DESCRIPTION:
415v5
Bank Station offset =      4373
LOB extended and blocked at watershed edge
END DESCRIPTION:
XS GIS Cut Line= 6
 3174917.585839413961455.8177315     3173951.645     13959600.14
     3173886.965     13959509.98     3173759.277    13959306.534
     3173656.863    13959164.045     3173581.165    13959052.725
#Sta/Elev= 30
   -1660    72.7    -600    72.5   18.33   72.96   95.67   73.47  204.34    71.9
  264.87   72.21  367.21   71.84  400.57   70.93  466.12   73.06  540.99   71.77
  555.35   74.24   569.6   74.65  602.09   62.55  617.29   61.44  623.75    58.3
   627.2    57.7  630.93   58.09  632.46    61.5  636.95   61.41  646.77   62.99
  678.42   73.91  689.29   73.92  702.57   72.33   720.7   74.02  726.37   72.82
  732.71   73.52  842.27   73.01  878.83   70.63   950.9   73.71 1093.28   74.42
#Mann= 3 ,-1 , 0
   -1660     .11       0   569.6     .04       0  678.42     .11       0
#Block Obstruct= 2 , 0
       0   -1655      77               0
Bank Sta=569.6,678.42
XS Rating Curve= 0
Exp/Cntr=.3,.1

Type RM Length L Ch R = 1 ,7015.351,50.58,48.26,48.68
BEGIN DESCRIPTION:
415s4u:  XS 4/4
Bank Station offset =      4462
END DESCRIPTION:
XS GIS Cut Line= 6
      3174894.74    13959048.272     3174721.412    13958794.698
     3174639.798    13958683.406     3174521.692    13958535.526
     3174431.649    13958442.692     3174222.368    13958242.316
#Sta/Elev= 30
       0   77.69    9.48   77.67   45.86   78.56    87.5   78.74  221.12   77.74
  253.89   76.71  268.53   75.39  286.49   74.11  363.38   75.28  452.57    74.8
  475.12   75.54  482.41   75.03  518.83   63.15  530.63   59.55  537.64   59.31
  542.15   59.56   553.7   62.97  564.61   65.42  578.54   66.87  586.44   72.71
  594.73   75.36  600.35   75.56  634.72   75.05  636.54   75.44  664.18   75.28
  765.41   74.43  798.91   73.28  842.17   76.85  910.56   78.03 1053.49   78.59
#Mann= 7 ,-1 , 0
       0     .11       0  268.53     .99       0  363.38     .11       0
  475.12     .04       0  600.35     .11       0  664.18     .99       0
  842.17     .11       0
Bank Sta=475.12,600.35
XS Rating Curve= 0
Exp/Cntr=.5,.3

Type RM Length L Ch R = 1 ,6967.086,58.97,59.45,58.92
BEGIN DESCRIPTION:
copy of 415s4u, XS 3/4, adjust elevations as needed
Bank Station offset =      4460
END DESCRIPTION:
XS GIS Cut Line= 6
      3174939.74    13959023.272     3174766.412    13958769.698
     3174684.798    13958658.406     3174558.704    13958503.863
     3174476.649    13958417.692     3174267.368    13958217.316
#Sta/Elev= 30
       0   78.11   27.45   77.86   91.66   78.21  222.84   77.31  276.14   75.44
   292.5   73.86  320.58   73.45  454.63    74.8  477.18   75.54  484.47   75.03
  532.69   59.55   539.7   59.31  544.21   59.56  555.76   62.97  566.67   65.42
   580.6   66.87   588.5   72.71  596.79   75.36  602.41   75.56  636.78   75.05
  642.55   74.46  655.05   74.27  763.23   74.57  809.69   72.92   839.2   75.61
  864.51   76.85  892.24   77.42  917.39   77.42  942.49   78.08 1053.37   78.61
#Mann= 6 ,-1 , 0
       0     .11       0  276.14     .99       0  477.18     .04       0
  602.41     .11       0  636.78     .99       0   839.2     .11       0
#XS Ineff= 2 , 0
       0   501.4      73   583.9       0      73
Permanent Ineff=
       F       F
Bank Sta=477.18,602.41
XS Rating Curve= 0
Exp/Cntr=.5,.3

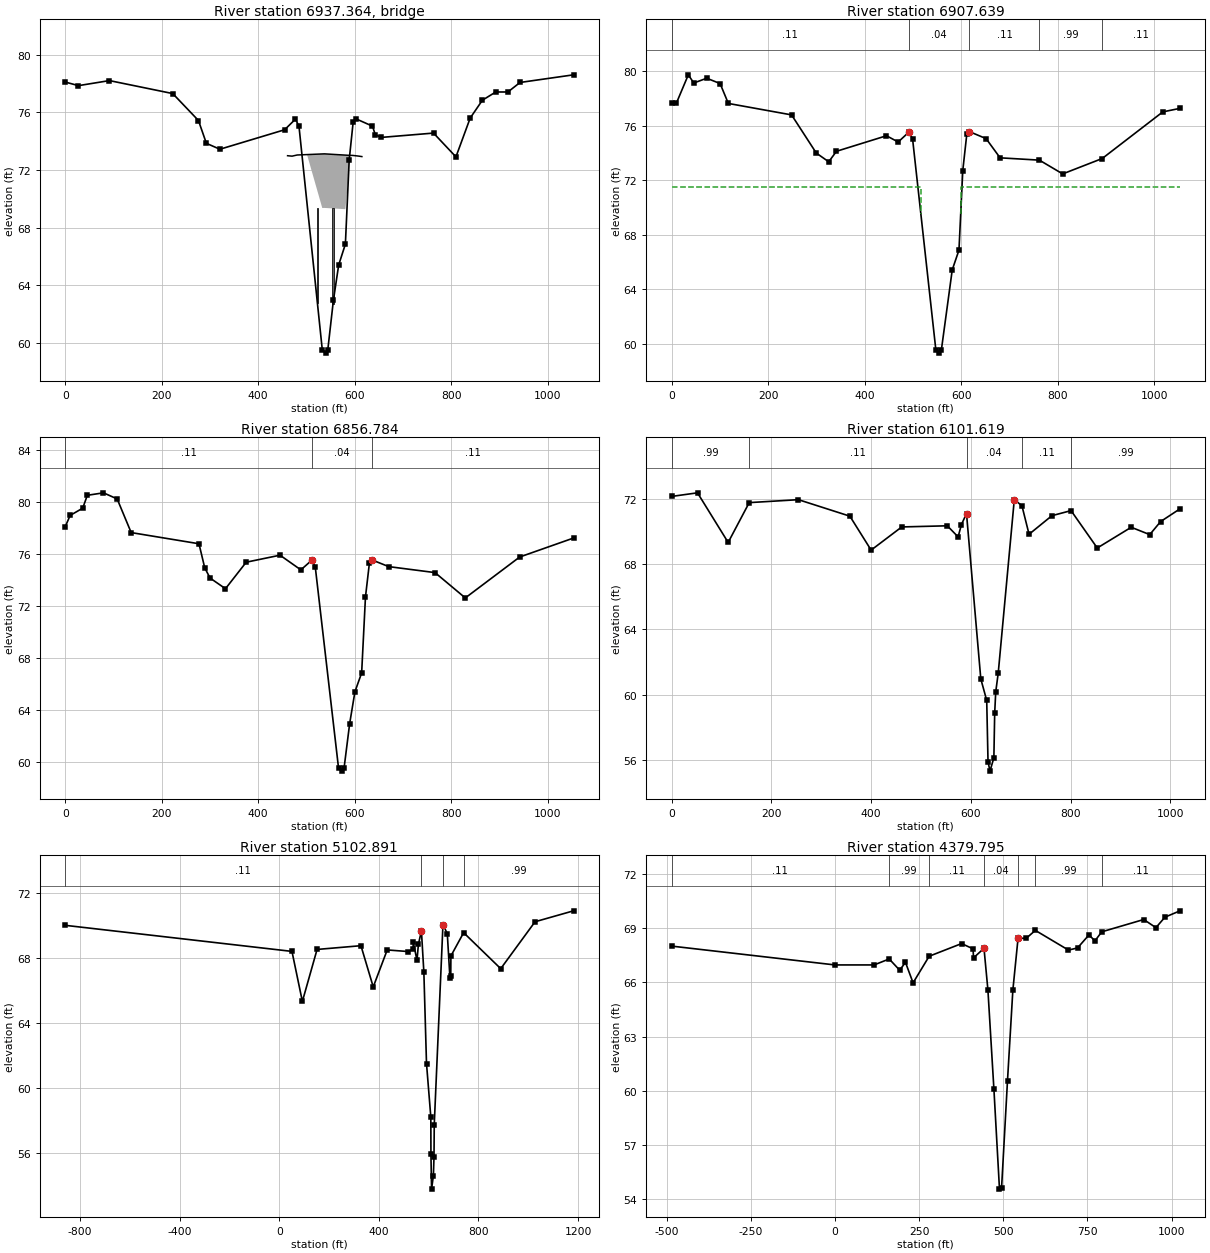
Type RM Length L Ch R = 3 ,6937.364,,,
BEGIN DESCRIPTION:
415s4: Mills Bridgeway "conc. bridge"
END DESCRIPTION:
Bridge Culvert--1,0,-1,-1, 0
Deck Dist Width WeirC Skew NumUp NumDn MinLoCord MaxHiCord MaxSubmerge Is_Ogee
10.6,38.1,2.6,0, 8, 8, 73.02, , .95, 0, 0,0,,
  460.81  470.09  480.61  537.14  586.86  596.01  606.61  614.75
      73   72.97   73.05   73.13   73.03   73.02   72.98   72.94
       0       0    69.3   69.38   69.28   69.27       0       0
  474.81  484.09  494.61  551.14  600.86  610.01  620.61  628.75
      73   72.97   73.05   73.13   73.03   73.02   72.98   72.94
       0       0    69.3   69.38   69.28   69.27       0       0
Pier Skew, UpSta & Num, DnSta & Num=  ,522.56, 4 ,536.56, 4 , 3 , 3 , 0 ,0,
    1.35    1.35    2.35    2.35
    58.5   67.01   67.01    69.4
    1.35    1.35    2.35    2.35
    58.5   67.01   67.01    69.4
Pier Skew, UpSta & Num, DnSta & Num=  ,554.98, 4 ,568.98, 4 , 3 , 3 , 0 ,0,
    1.35    1.35    2.35    2.35
    58.5   67.01   67.01   69.36
    1.35    1.35    2.35    2.35
    58.5   67.01   67.01   69.36
BR Coef=-1 , 0 , 0 ,, 0 ,,,.8,-1,,0,
WSPro=,,,, 1 ,,,, 0 ,,,, 0 ,,,,-1 ,-1 ,-1 , 0 , 0 , 0 , 0 , 0
BC Design=,, 0 ,, 0 ,,,,,,

Type RM Length L Ch R = 1 ,6907.639,50.37,50.85,49.36
BEGIN DESCRIPTION:
copy of 415s4u, XS 2/4, adjust elevations as needed
Bank Station offset =      4446
END DESCRIPTION:
XS GIS Cut Line= 6
      3174999.74    13959003.272     3174826.412    13958749.698
     3174744.798    13958638.406     3174618.704    13958483.863
     3174536.649    13958397.692     3174327.368    13958197.316
#Sta/Elev= 30
       0   77.69     9.5   77.63   34.46   79.73   45.84   79.13   72.58   79.48
  100.35   79.09  117.42   77.63  248.45   76.79  299.68   73.99  325.42   73.35
  341.53   74.12  445.16   75.26  469.37    74.8  491.92   75.54  499.21   75.03
  547.43   59.55  554.44   59.31  558.95   59.56  581.41   65.42  595.34   66.87
  603.24   72.71  611.53   75.36  617.15   75.56  651.52   75.05  680.56   73.64
  762.04   73.47  810.28   72.46  892.21   73.59  1017.7   77.01 1053.37   77.27
#Mann= 5 ,-1 , 0
       0     .11       0  491.92     .04       0  617.15     .11       0
  762.04     .99       0  892.21     .11       0
#XS Ineff= 2 , 0
       0  516.32    71.5   598.9       0    71.5
Permanent Ineff=
       F       F
Bank Sta=491.92,617.15
XS Rating Curve= 0
Exp/Cntr=.5,.3

Type RM Length L Ch R = 1 ,6856.784,717.23,755.16,800.7
BEGIN DESCRIPTION:
copy of 415s4u, XS 1/4, adjust elevations as needed
Bank Station offset =      4427
END DESCRIPTION:
XS GIS Cut Line= 6
      3175052.74    13958988.272     3174879.412    13958734.698
     3174797.798    13958623.406     3174671.704    13958468.863
     3174589.649    13958382.692     3174380.368    13958182.316
#Sta/Elev= 30
       0   78.12   10.24   78.99    36.3   79.55   45.84   80.54    79.3   80.73
  107.69   80.26  136.69   77.67  277.21   76.81  289.09   74.96  300.21   74.17
  332.12   73.35  375.05   75.39  445.16   75.93  488.33    74.8  510.88   75.54
  518.17   75.03  566.39   59.55   573.4   59.31  577.91   59.56  589.46   62.97
  600.37   65.42   614.3   66.87   622.2   72.71  630.49   75.36  636.11   75.56
  670.48   75.05  766.34   74.59  829.07   72.64  941.77   75.79 1053.37   77.25
#Mann= 3 ,-1 , 0
       0     .11       0  510.88     .04       0  636.11     .11       0
Bank Sta=510.88,636.11
XS Rating Curve= 0
Exp/Cntr=.3,.1

Type RM Length L Ch R = 1 ,6101.619,953.85,998.73,1037.97
BEGIN DESCRIPTION:
415v6
Bank Station offset =      4362
END DESCRIPTION:
XS GIS Cut Line= 6
     3175446.886     13958870.16     3175429.075    13958415.975
     3175416.878    13958318.445     3175403.076    13958243.228
     3175389.275     13958160.42     3175366.736    13957854.923
#Sta/Elev= 30
       0   72.15    51.8   72.37  113.29   69.33  155.52   71.77  254.24   71.95
  357.42   70.94  400.04   68.86  461.47   70.28  552.82   70.35  574.53   69.67
   581.1   70.42  591.35    71.1  620.03   60.97  631.89   59.65  634.51    55.9
  638.45   55.32  646.25   56.14  647.88   58.88     650   60.18  654.99   61.33
  687.23   71.96  702.61   71.57   716.8   69.83  762.66   70.97  801.04   71.28
  853.62   68.99  921.75   70.26  958.88   69.81  980.74   70.61 1019.57   71.39
#Mann= 5 ,-1 , 0
       0     .99       0  155.52     .11       0  591.35     .04       0
  702.61     .11       0  801.04     .99       0
Bank Sta=591.35,687.23
XS Rating Curve= 0
Exp/Cntr=.3,.1

Type RM Length L Ch R = 1 ,5102.891,686.99,723.1,757.95
BEGIN DESCRIPTION:
415v7
Bank Station offset =      4386
END DESCRIPTION:
XS GIS Cut Line= 6
 3175698.888766913959701.5681909     3176338.241    13958459.713
     3176448.765    13958206.694     3176533.368    13958068.657
      3176568.99    13957997.413     3176622.424     13957881.64
#Sta/Elev= 30
    -860      70   50.89    68.4   92.68   65.33  151.75   68.52  327.97   68.75
  377.38   66.22  433.51   68.49   518.6   68.39  536.77   68.53  538.36   68.95
  553.08   67.85   558.8   68.83  570.88   69.66  580.71   67.13  591.33   61.52
  608.73   58.22  609.13   55.95  611.72   53.81  619.02   54.64  621.49    55.8
  622.44   57.77  657.42   70.04  674.85   69.49  685.42   66.79  688.72   66.87
  689.35   68.12  740.49   69.55  889.47   67.34 1027.38   70.22 1181.95   70.89
#Mann= 4 ,-1 , 0
    -860     .11       0  570.88     .04       0  657.42     .11       0
  740.49     .99       0
Bank Sta=570.88,657.42
XS Rating Curve= 0
Exp/Cntr=.3,.1

Type RM Length L Ch R = 1 ,4379.795,46.11,53.03,51.45
BEGIN DESCRIPTION:
415s5u: XS 4/4
Bank Station offset =      4508
END DESCRIPTION:
XS GIS Cut Line= 6
 3176161.205748613959373.1889746     3176891.668    13958855.541
     3176959.178     13958803.42     3177057.818    13958727.264
     3177226.864    13958613.172     3177392.497    13958499.454
#Sta/Elev= 30
    -485      68       0   66.96  116.46   66.96  161.19   67.29  192.26   66.67
  209.56    67.1  232.12   65.97  279.89   67.44  376.23   68.14  410.28   67.85
  411.74   67.35  442.82   67.88  454.45   65.57  472.29   60.08  488.81   54.57
  495.04   54.65  512.62   60.57   528.5   65.56  543.93   68.43  568.78   68.44
  595.28   68.87  693.74   67.78  720.73    67.9   754.7   68.62  772.35   68.29
  792.61   68.79  917.33   69.47  953.53   69.02  980.39    69.6 1025.05   69.95
#Mann= 7 ,-1 , 0
    -485     .11       0  161.19     .99       0  279.89     .11       0
  442.82     .04       0  543.93     .11       0  595.28     .99       0
  792.61     .11       0
Bank Sta=442.82,543.93
XS Rating Curve= 0
Exp/Cntr=.5,.3