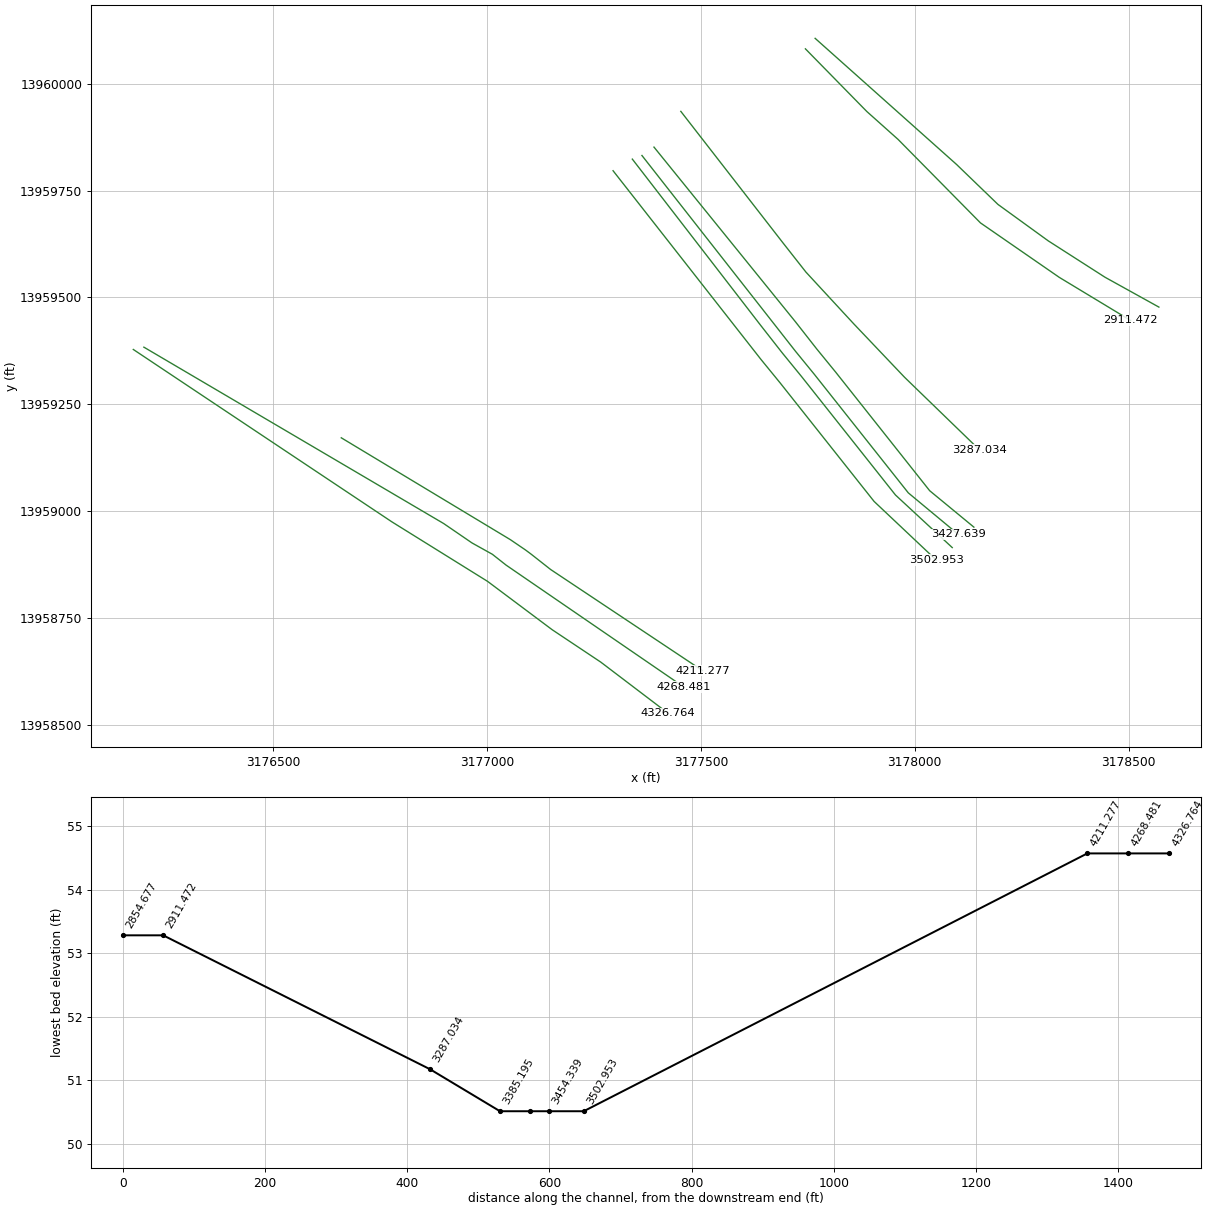
HEC-RAS study G103-80-031B.prj: G103-80-03.1B

--- G103-80-031B.g03 (geometry) --- (continued)

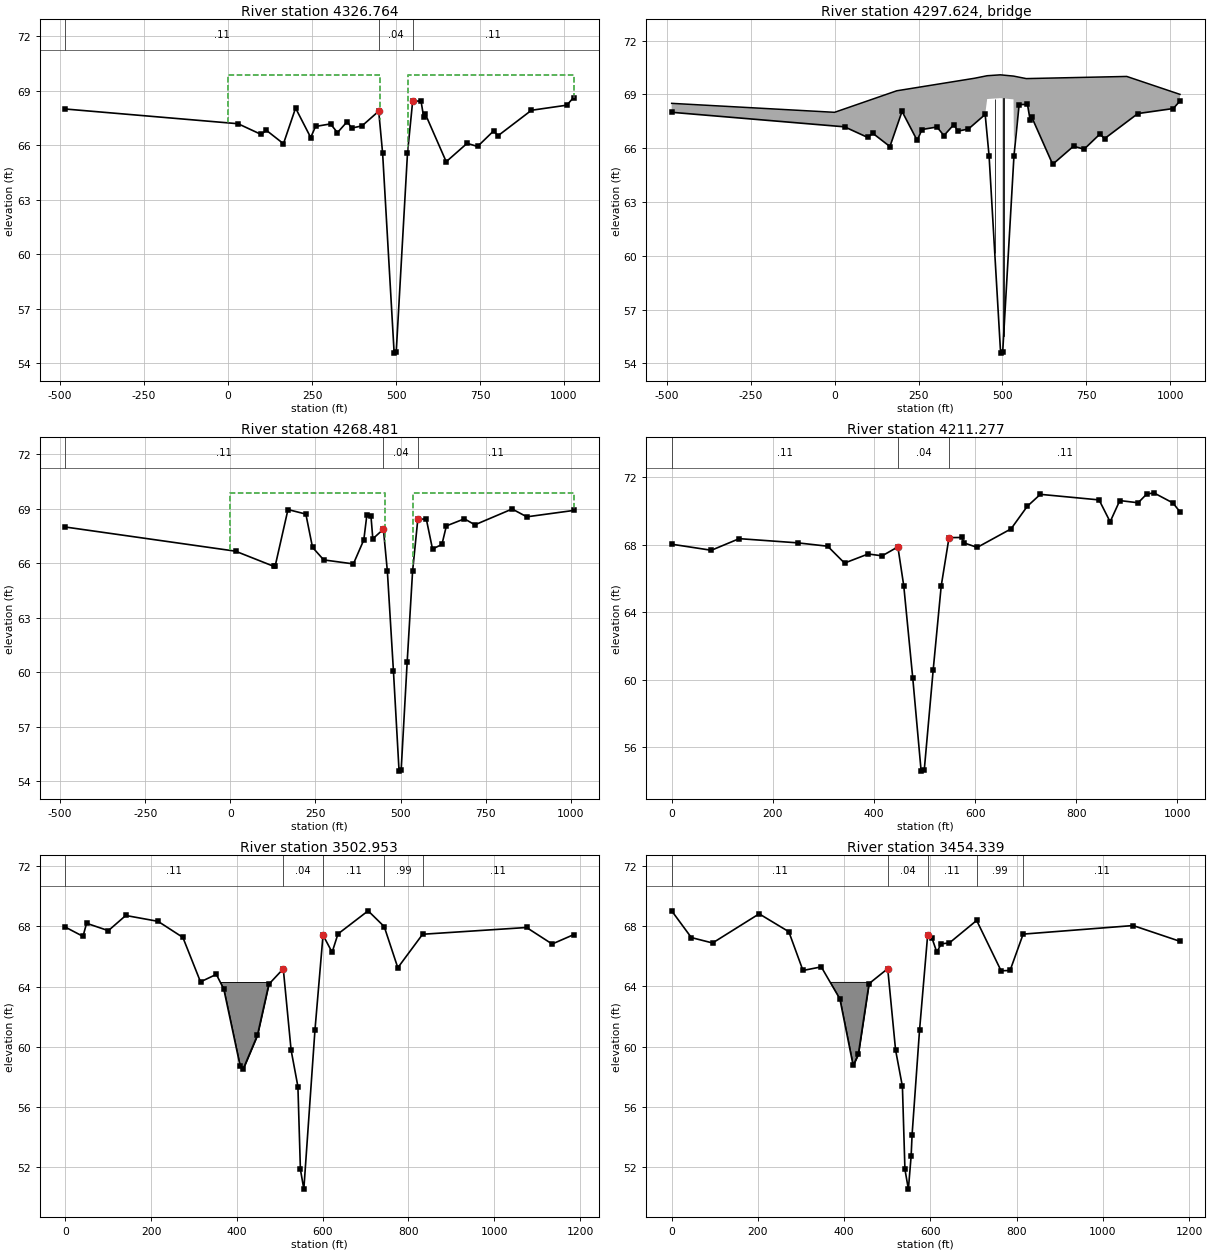
Type RM Length L Ch R = 1 ,4326.764,61.28,58.28,62.12
BEGIN DESCRIPTION:
copy of 415s5u, XS 3/4, adjust elevations as needed
Bank Station offset =      4502
END DESCRIPTION:
XS GIS Cut Line= 6
  3176173.07722513959378.4185218     3176777.614    13958975.392
     3177001.528    13958836.107     3177152.274    13958723.268
     3177265.994    13958647.455     3177423.792    13958527.564
#Sta/Elev= 30
    -485      68   29.63   67.19   98.48    66.6  113.79   66.83  164.85   66.09
  200.91   68.05  246.01   66.43  260.31   67.04  304.97   67.18  325.58    66.7
  354.87   67.31  367.53   66.95  398.65   67.07  448.44   67.88  460.07   65.57
  494.43   54.57  500.66   54.65  534.12   65.56  549.55   68.43   574.4   68.44
  582.14   67.58  587.33   67.72  649.45    65.1  711.57   66.11  742.92   65.94
  790.32   66.79  803.83   66.53   903.2   67.93 1008.48   68.21 1028.53   68.63
#Mann= 3 ,-1 , 0
    -485     .11       0  448.44     .04       0  549.55     .11       0
#XS Ineff= 2 , 0
       0     451   69.88     535       0   69.88
Permanent Ineff=
       F       F
Bank Sta=448.44,549.55
XS Rating Curve= 0
Exp/Cntr=.5,.3

Type RM Length L Ch R = 3 ,4297.624,,,
BEGIN DESCRIPTION:
415s5: Mills Branch Rd. "conc. bridge"
END DESCRIPTION:
Bridge Culvert--1,0,-1,-1, 0
Deck Dist Width WeirC Skew NumUp NumDn MinLoCord MaxHiCord MaxSubmerge Is_Ogee
14,30.1,2.6,0, 10, 10, 70.02, , .95, 0, 0,0,,
    -485       0     185     417  454.36  493.47  532.78  570.84     870 1028.53
    68.5      68    69.2    69.9   70.04   70.09   70.02   69.88      70      69
       0       0       0       0   68.74   68.79   68.72       0       0       0
    -485       0     185     418  455.36  494.47  533.78  571.84     850 1007.97
    68.5      68    69.2    69.9   70.04   70.09   70.02   69.88      70      69
       0       0       0       0   68.74   68.79   68.72       0       0       0
Pier Skew, UpSta & Num, DnSta & Num=  ,477, 2 ,478, 2 , 0 , 0 , 0 ,0,
     1.4     1.4
      54   68.79
     1.4     1.4
      54   68.79
Pier Skew, UpSta & Num, DnSta & Num=  ,503.36, 2 ,504.36, 2 , 0 , 0 , 0 ,0,
     1.4     1.4
      54   68.79
     1.4     1.4
      54   68.79
BR Coef=-1 , 0 , 0 ,, 0 ,,,.8,-1,,0,
WSPro=,,,, 1 ,,,, 0 ,,,, 0 ,,,,-1 ,-1 ,-1 , 0 , 0 , 0 , 0 , 0
BC Design=,, 0 ,, 0 ,,,,,,

Type RM Length L Ch R = 1 ,4268.481,56.15,57.2,52.91
BEGIN DESCRIPTION:
copy of 415s5u, XS 2/4, adjust elevations as needed
Bank Station offset =      4501
END DESCRIPTION:
XS GIS Cut Line= 6
 3176197.773250513959383.8219449     3176898.742    13958971.417
     3176965.103    13958925.977     3177012.517    13958899.582
     3177044.779    13958874.164      3177460.35    13958589.153
#Sta/Elev= 30
    -485      68   15.16   66.67  128.33   65.83     132   65.88  169.27   68.96
  221.78   68.71  241.38   66.88  274.26   66.19   361.4   65.97  391.99   67.29
  400.93   68.65  412.93   68.62  418.47   67.35  449.55   67.88  461.18   65.57
  479.02   60.08  495.54   54.57  501.77   54.65  519.35   60.57  535.23   65.56
  550.66   68.43  575.51   68.44  593.76   66.79  621.41   67.04  634.49   68.06
  687.52   68.45  718.22   68.12  827.67   68.99  870.75   68.56 1007.97   68.91
#Mann= 3 ,-1 , 0
    -485     .11       0  449.55     .04       0  550.66     .11       0
#XS Ineff= 2 , 0
       0     453   69.88     537       0   69.88
Permanent Ineff=
       F       F
Bank Sta=449.55,550.66
XS Rating Curve= 0
Exp/Cntr=.5,.3

Type RM Length L Ch R = 1 ,4211.277,732.4,708.33,695.7
BEGIN DESCRIPTION:
copy of 415s5u, XS 1/4, adjust elevations as needed
Bank Station offset =      4503
END DESCRIPTION:
XS GIS Cut Line= 6
     3176659.342    13959171.879     3177054.555    13958933.798
     3177089.749    13958909.847     3177102.947     13958900.07
     3177148.894    13958863.899     3177503.791    13958627.643
#Sta/Elev= 30
       0   68.04   78.47   67.68   133.6   68.37  249.38   68.12  308.49   67.92
  341.83   66.92  388.59   67.46  416.23   67.35  447.31   67.88  458.94   65.57
  476.78   60.08   493.3   54.57  499.53   54.65  517.11   60.57  532.99   65.56
  548.42   68.43  573.27   68.44  578.86   68.11  604.17   67.85  671.07   68.95
  703.21   70.29  729.04      71  845.17   70.67  867.04   69.37  886.15   70.63
  922.46    70.5  939.12   71.01  953.38   71.09  991.15   70.49  1005.2   69.96
#Mann= 3 ,-1 , 0
       0     .11       0  447.31     .04       0  548.42     .11       0
Bank Sta=447.31,548.42
XS Rating Curve= 0
Exp/Cntr=.3,.1

Type RM Length L Ch R = 1 ,3502.953,48.75,48.61,48.23
BEGIN DESCRIPTION:
415s6u:  XS 4/4
Bank Station offset =      4444
END DESCRIPTION:
XS GIS Cut Line= 6
     3177294.795    13959796.341     3177591.373     13959417.95
     3177640.942    13959354.707      3177685.48    13959300.171
     3177905.098    13959023.142     3178050.246     13958886.21
#Sta/Elev= 30
       0   67.96   41.45   67.34   49.79   68.21  100.51   67.72  141.13   68.73
  216.32   68.34   274.2   67.27   315.3   64.31  352.21   64.81  369.63   63.82
  407.74    58.7  414.76   58.51  447.95   60.76  474.48   64.15  508.19   65.18
  526.41   59.77  542.28   57.34  548.12   51.82  556.11   50.51  581.96   61.08
  600.81   67.42  622.02   66.28   635.6    67.5  705.92   69.04  743.42   67.99
  775.09   65.25  832.89   67.48 1075.15   67.93 1134.74   66.83  1184.6   67.45
#Mann= 5 ,-1 , 0
       0     .11       0  508.19     .04       0  600.81     .11       0
  743.42     .99       0  832.89     .11       0
#Block Obstruct= 2 , 0
       0  479.78    64.3               0
Bank Sta=508.19,600.81
XS Rating Curve= 0
Exp/Cntr=.5,.3

Type RM Length L Ch R = 1 ,3454.339,26.6,26.7,26.41
BEGIN DESCRIPTION:
copy of 415s6u, XS 3/4, adjust elevations as needed
Bank Station offset =      4451
END DESCRIPTION:
XS GIS Cut Line= 6
     3177339.853    13959823.476     3177641.373     13959432.95
     3177690.942    13959369.707      3177735.48    13959315.171
     3177955.098    13959038.142     3178087.847    13958915.198
#Sta/Elev= 30
       0   69.03   45.59   67.25   94.83   66.89  202.85   68.83  271.63   67.64
  304.41   65.06  346.83    65.3  389.96   63.17  420.77   58.74  432.74   59.48
  457.46   64.18  500.91   65.18  519.13   59.77     535   57.34  540.84   51.82
  548.83   50.51  555.16   52.69  557.44   54.14  574.68   61.08  593.53   67.42
  603.49   67.22  614.74   66.28   624.9   66.83  644.15    66.9  707.16   68.39
  763.77   65.04  784.63   65.06  814.91   67.48 1069.91   68.05  1178.6      67
#Mann= 5 ,-1 , 0
       0     .11       0  500.91     .04       0  593.53     .11       0
  707.16     .99       0  814.91     .11       0
#Block Obstruct= 2 , 0
       0   472.5    64.3               0
Bank Sta=500.91,593.53
XS Rating Curve= 0
Exp/Cntr=.5,.3

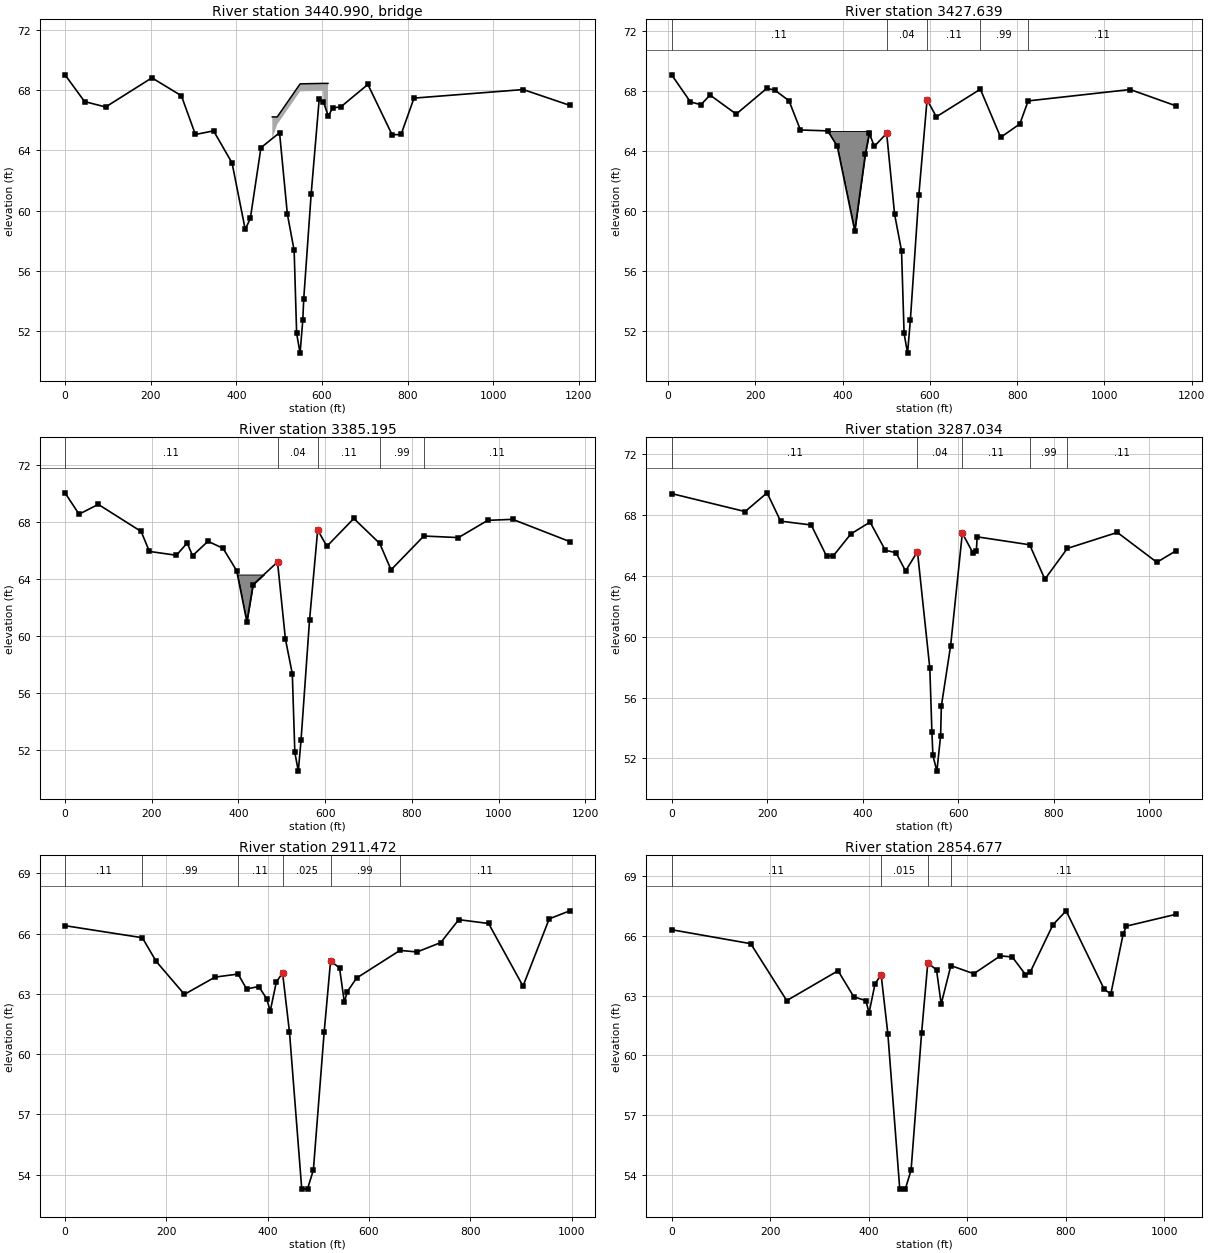
Type RM Length L Ch R = 3 ,3440.990,,,
BEGIN DESCRIPTION:
415s6: FOOTBRIDGE "wooden footbridge" (nr Maple Bend)
END DESCRIPTION:
Bridge Culvert--1,0,-1,-1, 0
Deck Dist Width WeirC Skew NumUp NumDn MinLoCord MaxHiCord MaxSubmerge Is_Ogee
9.85,7,2.6,0, 5, 5, , , .95, 0, 0,0,,
     484  495.47     549  602.49     614
   66.23   66.23   68.43   68.46   68.46
       0   65.73   67.93   67.96       0
     484  495.47     549  602.49     614
   66.23   66.23   68.43   68.46   68.46
       0   65.73   67.93   67.96       0
BR Coef=-1 , 0 , 0 ,, 0 ,,,.8,-1,,0,
WSPro=,,,, 1 ,,,, 0 ,,,, 0 ,,,,-1 ,-1 ,-1 , 0 , 0 , 0 , 0 , 0
BC Design=,, 0 ,, 0 ,,,,,,

Type RM Length L Ch R = 1 ,3427.639,41.56,42.44,41.94
BEGIN DESCRIPTION:
copy of 415s6u, XS 2/4, adjust elevations as needed
Bank Station offset =      4459
END DESCRIPTION:
XS GIS Cut Line= 6
     3177362.349    13959831.912     3177671.373     13959437.95
     3177720.942    13959374.707      3177765.48    13959320.171
     3177985.098    13959043.142     3178101.907     13958946.13
#Sta/Elev= 30
     8.1   69.08   51.19   67.27   75.24   67.09   96.15   67.73  156.06   66.46
  226.27   68.18  244.84   68.05  277.13   67.35  303.22    65.4  365.85   65.34
  387.67   64.31  427.76   58.67  451.78   63.77  461.17   65.19   472.5    64.3
  500.91   65.18  519.13   59.77     535   57.34  540.84   51.82  548.83   50.51
  555.16   52.69  574.68   61.08  593.53   67.42  614.74   66.28  715.68   68.12
  762.17   64.91  805.99    65.8  825.29   67.34 1059.05    68.1 1164.93      67
#Mann= 5 ,-1 , 0
     8.1     .11       0  500.91     .04       0  593.53     .11       0
  715.68     .99       0  825.29     .11       0
#Block Obstruct= 2 , 0
       0   464.1   65.33               0
Bank Sta=500.91,593.53
XS Rating Curve= 0
Exp/Cntr=.5,.3

Type RM Length L Ch R = 1 ,3385.195,93.15,98.16,103.3
BEGIN DESCRIPTION:
copy of 415s6u, XS 1/4, adjust elevations as needed
Bank Station offset =      4462
END DESCRIPTION:
XS GIS Cut Line= 6
     3177390.469    13959851.596     3177721.373     13959442.95
     3177770.942    13959379.707      3177815.48    13959325.171
     3178035.098    13959048.142     3178138.463    13958963.002
#Sta/Elev= 30
       0   70.03   32.31   68.53   76.67   69.22  175.52   67.32  194.52   65.92
  256.81   65.65  281.71   66.51  294.13   65.62  329.63   66.63  364.38   66.14
  395.82   64.57  419.33   60.98  433.64   63.59  490.05   65.18  508.27   59.77
  524.14   57.34  529.98   51.82  537.97   50.51   544.3   52.69  563.82   61.08
  582.67   67.42  603.88   66.28     666   68.23  725.77   66.48  751.86   64.63
  827.45      67  907.27   66.89  974.87    68.1 1032.44   68.17 1164.02   66.61
#Mann= 5 ,-1 , 0
       0     .11       0  490.05     .04       0  582.67     .11       0
  725.77     .99       0  827.45     .11       0
#Block Obstruct= 2 , 0
       0  461.64    64.3               0
Bank Sta=490.05,582.67
XS Rating Curve= 0
Exp/Cntr=.3,.1

Type RM Length L Ch R = 1 ,3287.034,371.71,375.56,377.15
BEGIN DESCRIPTION:
415v8
Bank Station offset =      4444
Blocked low area in ROB.  Area determined unavailable to flow or storage.
END DESCRIPTION:
XS GIS Cut Line= 6
      3177453.22    13959935.113     3177691.483    13959628.384
     3177745.697    13959559.396      3177856.95    13959439.006
     3177976.303    13959313.439     3178151.576    13959143.643
#Sta/Elev= 30
       0   69.39  153.84   68.21  199.96   69.44  228.23   67.58  292.37   67.33
  324.44   65.29  338.81   65.31  375.41   66.74  415.67   67.52  447.56   65.67
  469.92   65.51  490.01   64.31  514.92   65.58  540.84   57.92  545.18   53.75
  547.29    52.2  555.61   51.17  563.47    53.5  564.93   55.43  584.43   59.41
  608.91   66.79  631.26   65.49   638.2   65.61  640.06   66.55  749.99   66.03
  781.82   63.77  828.88   65.79  933.62   66.84 1016.42   64.88 1057.33   65.65
#Mann= 5 ,-1 , 0
       0     .11       0  514.92     .04       0  608.91     .11       0
  749.99     .99       0  828.88     .11       0
#Block Obstruct= 2 , 0
       0                     930       0    66.9
Bank Sta=514.92,608.91
XS Rating Curve= 0
Exp/Cntr=.3,.1

Type RM Length L Ch R = 1 ,2911.472,54.25,56.79,58.95
BEGIN DESCRIPTION:
415s7u:  XS 4/4 Energy dissipater / Grade Control structure.
Bank Station offset =      4521
Expansion/ Contrancion COfficients changed to model the energy disipator.    Blocked low area in ROB.  Area determined unavailable to flow or storage.
END DESCRIPTION:
XS GIS Cut Line= 6
     3177744.528     13960081.32     3177887.881    13959935.044
     3177961.262    13959869.507     3178153.902    13959674.302
     3178338.285    13959546.891     3178504.898    13959446.191
#Sta/Elev= 30
       0    66.4  152.59    65.8  179.99   64.62  235.62   62.98  296.22   63.84
   341.6   63.99   358.3   63.25  382.42   63.37  398.29   62.75     405   62.14
     417   63.59  429.39   64.05  443.05   61.09  467.24   53.28  478.71    53.3
  490.18   54.23  511.52   61.11  524.16   64.65  541.88   64.29  551.31   62.58
  556.81    63.1  575.38   63.79  661.18   65.17  694.74   65.09  741.63   65.56
  777.13    66.7  835.99   66.51  903.95   63.39  955.65   66.74  996.26   67.14
#Mann= 6 ,-1 , 0
       0     .11       0  152.59     .99       0   341.6     .11       0
  429.39    .025       0  524.16     .99       0  661.18     .11       0
#Block Obstruct= 2 , 0
       0                     835       0    66.4
Bank Sta=429.39,524.16
XS Rating Curve= 0
Exp/Cntr=.8,.6

Type RM Length L Ch R = 1 ,2854.677,53.85,46.02,46.02
BEGIN DESCRIPTION:
copy of 415s7u, XS 3/4 Energy dissipater / Grade Control structure.
Bank Station offset =      4451
Expansion/ Contraction Coefficients changed to 0.6/0.8 to model the energy disipator.  Ineffective flow set at channel bank stations with elevations at  min. top of wall.
END DESCRIPTION:
XS GIS Cut Line= 6
     3177767.235    13960105.887     3178097.614    13959811.271
     3178194.684    13959717.607      3178312.19    13959632.458
     3178445.022    13959547.309     3178571.043    13959477.486
#Sta/Elev= 30
       0   66.31  160.47   65.61  233.64   62.75  337.76   64.25  369.68   62.94
  394.08   62.75  400.79   62.14  412.79   63.59  425.18   64.05  438.84   61.09
  463.03   53.28   474.5    53.3  485.97   54.23  507.31   61.11  519.95   64.65
  537.67   64.29   547.1   62.58   566.8   64.51  613.32    64.1  667.33      65
  691.39   64.94  718.24   64.06  727.83   64.18   773.9   66.56  800.76   67.26
  878.22   63.31  891.51   63.09  916.36   66.08  922.79   66.49 1024.52   67.09
#Mann= 4 ,-1 , 0
       0     .11       0  425.18    .015       0  519.95     .99       0
   566.8     .11       0
#XS Ineff= 2 , 0
       0  425.18   61.91  519.95       0   61.91
Permanent Ineff=
       F       F
#Block Obstruct= 2 , 0
       0                  796.23       0   67.27
Bank Sta=425.18,519.95
XS Rating Curve= 0
Exp/Cntr=.8,.6