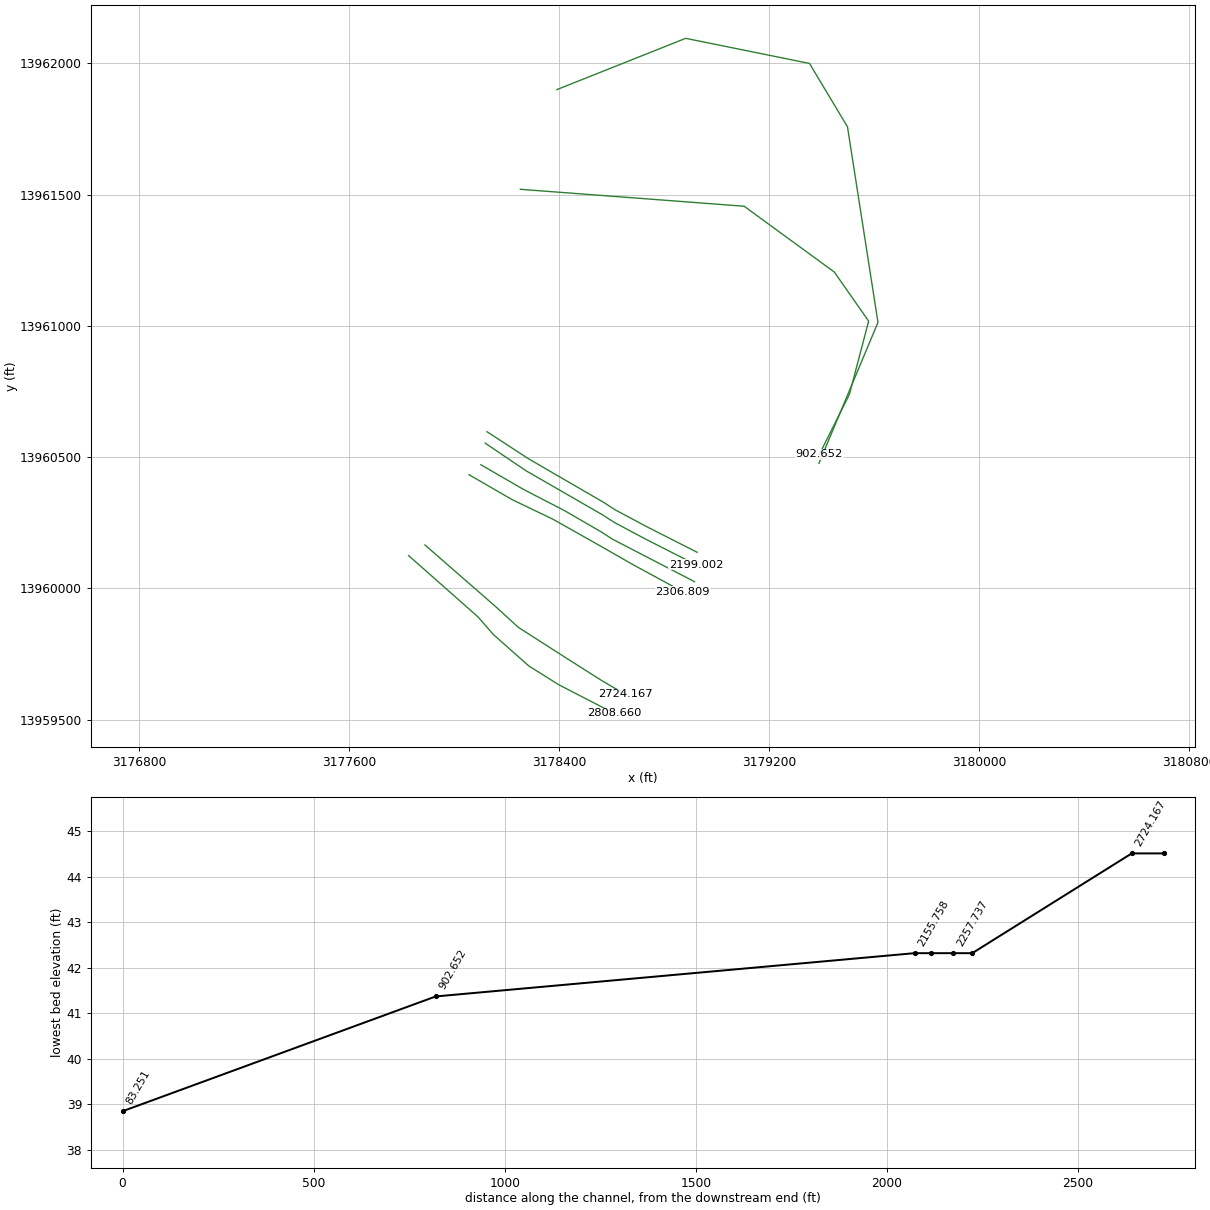
HEC-RAS study G103-80-031B.prj: G103-80-03.1B

--- G103-80-031B.g03 (geometry) --- (continued)

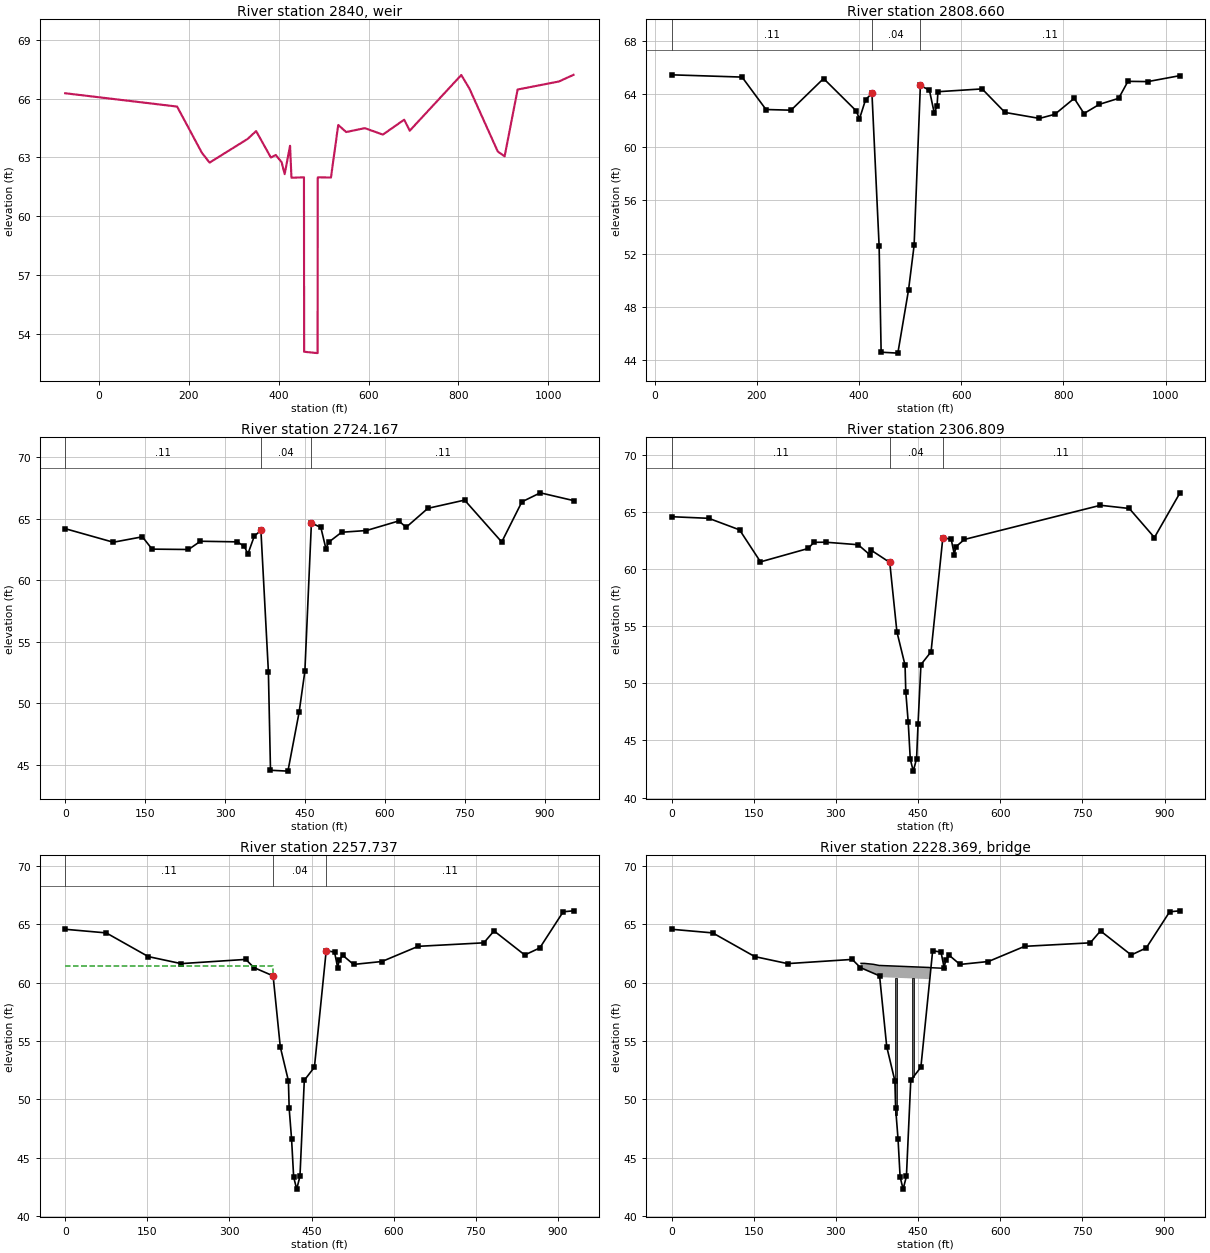
Type RM Length L Ch R = 5 ,2840    ,,,
BEGIN DESCRIPTION:
Energy dissipater / Grade Control Structure, modeled as inline weir.
Used n = 0.015 u/s of weir due to concrete lined channel.  Used weir coefficient of 3.0 due to high u/s head and the downstream slope of weir, 4H:1V.  Values used were based on engineering judgement and comparison to Tables 5-4 to 5-13 (pp. 5-40 to 5-44) in "Handbook of Hydraulics", 6th Edition (1976), Brater, E.F., and King, H.W.  McGraw-Hill, Inc., New York, N.Y.
END DESCRIPTION:
IW Pilot Flow=0
#Inline Weir SE= 30
  -74.79   66.27   174.1   65.59  229.28   63.23   246.3   62.73  331.08   63.94
  349.83   64.34   382.7   62.99  393.46   63.12  406.63   62.75  413.34   62.14
  425.34   63.59  428.44   61.96  456.28   61.98  456.68   53.08  486.55   53.01
  486.97   61.98  516.32   61.97   532.5   64.65  550.22   64.29  591.61   64.49
  631.81   64.16  679.19   64.92  691.54   64.36  806.21    67.2  824.27   66.51
  887.32    63.3  902.61   63.05   931.5   66.46 1023.39   66.87 1055.88   67.21
IW Dist,WD,Coef,Skew,MaxSub,Min_El,Is_Ogee,SpillHt,DesHd
5,15,3,0,.95,, 0 ,,,0,2.5,

Type RM Length L Ch R = 1 ,2808.660,76.29,84.49,87.24
BEGIN DESCRIPTION:
copy of 415s7u, XS 2/4 Energy dissipater / Grade Control structure.
Cross section data changed to reflect energy dissipater.
Channel geometry and dissipater lowered 8.5'.  Sketch in recon notes.
Expansion/ Contrancion Coefficients changed to model the energy dissipater.
Bank Station offset =      4559
END DESCRIPTION:
XS GIS Cut Line= 6
      3177826.97    13960125.175     3178090.933    13959891.866
     3178150.537    13959823.747     3178285.073    13959704.538
     3178399.172    13959633.013     3178610.342    13959524.022
#Sta/Elev= 30
   33.19   65.45  170.96   65.28  217.81   62.84  266.82   62.79  330.51   65.17
  394.08   62.75  400.79   62.14  412.79   63.59  425.18   64.05   439.2   52.59
  443.16   44.58  475.86   44.51   496.8   49.27  507.67   52.61  519.95   64.65
  537.67   64.29   547.1   62.58   552.6    63.1  554.35   64.18  640.82   64.39
  685.58   62.62  753.01   62.17  783.17   62.48  821.05   63.68  840.18   62.54
  870.33   63.23  908.01   63.68  926.23   64.96  965.06   64.94  1028.1   65.39
#Mann= 3 ,-1 , 0
   33.19     .11       0  425.18     .04       0  519.95     .11       0
Bank Sta=425.18,519.95
XS Rating Curve= 0
Exp/Cntr=.8,.6

Type RM Length L Ch R = 1 ,2724.167,399.08,417.36,427.82
BEGIN DESCRIPTION:
copy of 415s7u, XS 1/4 Energy dissipater / Grade Control structure.
Bank Station offset =      4583
Cross section data changed to reflect energy disipator.
Channel geometry lowered 8.5'.  Sketch in recon notes.
END DESCRIPTION:
XS GIS Cut Line= 6
     3177889.415    13960165.448     3178156.089    13959932.834
     3178244.866    13959851.814     3178437.584    13959728.365
     3178567.828    13959645.737      3178651.64    13959597.106
#Sta/Elev= 30
       0   64.19   90.31   63.09  144.86   63.53  163.06   62.53  231.38    62.5
  253.82   63.17  323.05   63.12  336.22   62.75  342.93   62.14  354.93   63.59
  367.32   64.05  381.34   52.59   385.3   44.58     418   44.51  438.94   49.27
  449.81   52.61  462.09   64.65  479.81   64.29  489.24   62.58  494.74    63.1
  518.82    63.9  565.38   64.04   626.3   64.82  639.82    64.3  680.62   65.84
  749.62   66.51   819.3   63.11  857.17   66.37  891.71    67.1  954.07   66.47
#Mann= 3 ,-1 , 0
       0     .11       0  367.32     .04       0  462.09     .11       0
Bank Sta=367.32,462.09
XS Rating Curve= 0
Exp/Cntr=.3,.1

Type RM Length L Ch R = 1 ,2306.809,50.26,49.07,49.62
BEGIN DESCRIPTION:
415s8u:  XS 4/4
Bank Station offset =      4559
END DESCRIPTION:
XS GIS Cut Line= 6
     3178057.143    13960433.173     3178221.754    13960338.031
     3178376.849    13960263.576     3178566.076    13960156.809
      3178679.34    13960091.871     3178871.133    13959987.668
#Sta/Elev= 30
       0   64.58    67.7   64.44  123.99   63.43  162.21   60.63  249.23    61.8
  259.72   62.34  281.12   62.35  340.55   62.13  362.17   61.24  364.32   61.65
  398.24   60.58  411.31   54.51  426.19   51.59  427.52   49.26  431.95   46.61
  435.74   43.36  441.27   42.32  447.26   43.42  449.93   46.46   455.2   51.64
  473.66   52.76  495.17   62.73  510.41   62.62  516.19   61.27  519.05   61.95
  534.53   62.59  783.08   65.58  835.67    65.3  881.62   62.76  928.29   66.67
#Mann= 3 ,-1 , 0
       0     .11       0  398.24     .04       0  495.17     .11       0
Bank Sta=398.24,495.17
XS Rating Curve= 0
Exp/Cntr=.5,.3

Type RM Length L Ch R = 1 ,2257.737,58.72,58.74,59.01
BEGIN DESCRIPTION:
copy of 415s8u,  XS 3/4, adjust elevations as needed
Bank Station offset =      4577
END DESCRIPTION:
XS GIS Cut Line= 6
     3178102.143    13960471.173     3178266.754    13960376.031
     3178419.047    13960297.423      3178561.84    13960214.645
     3178603.229    13960187.742     3178916.133    13960025.668
#Sta/Elev= 30
       0   64.57   74.94   64.26   151.8   62.23  211.71   61.63  329.76   61.99
  344.63   61.29  379.69   60.58  392.76   54.51  407.64   51.59  408.97   49.26
   413.4   46.61  417.19   43.36  422.72   42.32  428.71   43.42  436.65   51.64
  455.11   52.76  476.62   62.73  491.86   62.62  497.64   61.27   500.5   61.95
  507.13   62.33  526.56   61.56  578.44   61.81  644.59   63.11  764.51   63.41
  783.15   64.43  839.21   62.37  866.67   62.97  909.46   66.07  928.33   66.15
#Mann= 3 ,-1 , 0
       0     .11       0  379.69     .04       0  476.62     .11       0
#XS Ineff= 2 , 0
       0  379.69   61.45     475       0   61.25
Permanent Ineff=
       F       F
Bank Sta=379.69,476.62
XS Rating Curve= 0
Exp/Cntr=.5,.3

Type RM Length L Ch R = 3 ,2228.369,,,
BEGIN DESCRIPTION:
415s8: Maple Bend Dr. "conc. bridge"
END DESCRIPTION:
Bridge Culvert--1,0,-1,-1, 0
Deck Dist Width WeirC Skew NumUp NumDn MinLoCord MaxHiCord MaxSubmerge Is_Ogee
10,38,2.6,0, 9, 9, 61.47, , .95, 0, 0,0,,
   345.8  352.04   368.4  379.15  381.07  469.96  472.57  482.76  501.01
   61.65   61.65   61.57   61.47   61.47    61.3   61.28   61.26   61.22
       0       0       0   60.47   60.47    60.3   60.28       0       0
     375  381.04   397.4  408.15  410.07  498.96  501.57  511.76  530.01
    61.6   61.65   61.57   61.47   61.47    61.3   61.28   61.26   61.22
       0       0       0   60.47   60.47    60.3   60.28       0       0
Pier Skew, UpSta & Num, DnSta & Num=  ,410.02, 4 ,439.02, 4 , 3 , 3 , 0 ,0,
     1.3     1.3       3       3
      47   57.41   57.41    60.5
     1.3     1.3       3       3
      47   57.41   57.41    60.5
Pier Skew, UpSta & Num, DnSta & Num=  ,440.96, 4 ,469.96, 4 , 3 , 3 , 0 ,0,
     1.3     1.3       3       3
      47   57.36   57.36   60.36
     1.3     1.3       3       3
      47   57.36   57.36   60.36
BR Coef=-1 , 0 , 0 ,, 0 ,,,.8,-1,,0,
WSPro=,,,, 1 ,,,, 0 ,,,, 0 ,,,,-1 ,-1 ,-1 , 0 , 0 , 0 , 0 , 0
BC Design=,, 0 ,, 0 ,,,,,,

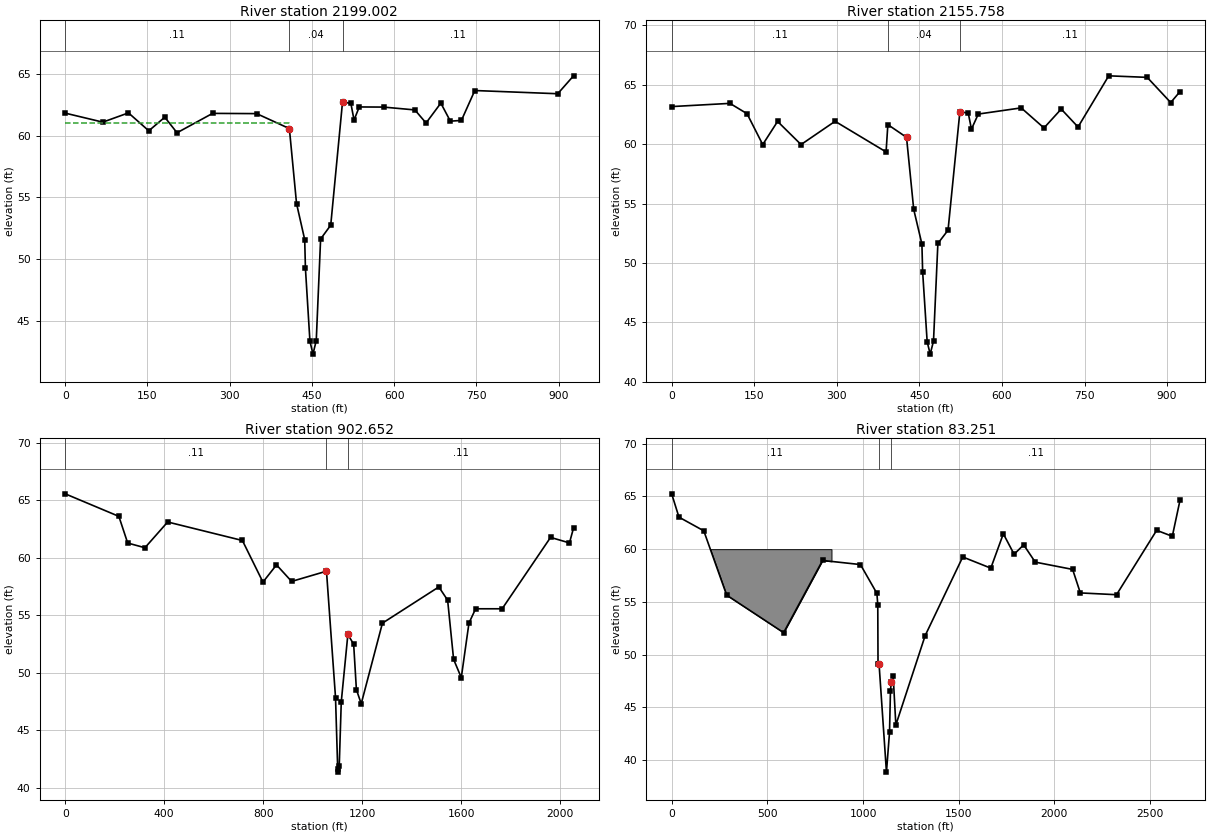
Type RM Length L Ch R = 1 ,2199.002,43.16,43.24,42.17
BEGIN DESCRIPTION:
copy of 415s8u,  XS 2/4, adjust elevations as needed
Bank Station offset =      4548
END DESCRIPTION:
XS GIS Cut Line= 6
      3178118.74    13960553.337     3178274.638    13960448.001
      3178566.84    13960279.645     3178608.229    13960252.742
     3178728.258    13960188.589     3178921.133    13960090.668
#Sta/Elev= 30
       0   61.83   68.58    61.1  115.37   61.85  152.46    60.4  181.59    61.5
  203.96   60.24  268.79   61.81  349.13   61.79  408.87   60.58  421.94   54.51
  436.82   51.59  438.15   49.26  446.37   43.36   451.9   42.32  457.89   43.42
  465.83   51.64  484.29   52.76   505.8   62.73  521.04   62.62  526.82   61.27
  536.31   62.33  580.56   62.32  637.74   62.09  658.15   61.03   685.1   62.64
  702.49   61.18  722.65   61.24  747.06   63.66  898.33    63.4  927.15   64.85
#Mann= 3 ,-1 , 0
       0     .11       0  408.87     .04       0   505.8     .11       0
#XS Ineff= 2 , 0
       0     408      61     505       0      61
Permanent Ineff=
       F       F
Bank Sta=408.87,505.8
XS Rating Curve= 0
Exp/Cntr=.5,.3

Type RM Length L Ch R = 1 ,2155.758,1262.32,1253.11,1239.18
BEGIN DESCRIPTION:
copy of 415s8u,  XS 1/4, adjust elevations as needed
Bank Station offset =      4530
END DESCRIPTION:
XS GIS Cut Line= 6
     3178125.763    13960596.876     3178283.065    13960494.349
      3178571.84    13960326.645     3178613.229    13960299.742
     3178733.258    13960235.589     3178926.133    13960137.668
#Sta/Elev= 30
       0   63.17  105.88   63.44  136.92   62.57  165.42   59.97  192.41   61.92
  235.04   59.97  296.87   61.93  389.52   59.35  392.73   61.65  426.65   60.58
  439.72   54.51   454.6   51.59  455.93   49.26  464.15   43.36  469.68   42.32
  475.67   43.42  483.61   51.64  502.07   52.76  523.58   62.73  538.82   62.62
   544.6   61.27  557.04   62.54  635.01   63.06  676.39   61.37  707.68   62.96
  738.25   61.45  793.99   65.76  863.89   65.63  906.61   63.51  923.48   64.43
#Mann= 3 ,-1 , 0
       0     .11       0  392.73     .04       0  523.58     .11       0
Bank Sta=426.65,523.58
XS Rating Curve= 0
Exp/Cntr=.3,.1

Type RM Length L Ch R = 1 ,902.652 ,686.14,819.4,639.6
BEGIN DESCRIPTION:
415v9
Bank Station offset =      3896
block on ROB due to low area determined not available for flow or storage
END DESCRIPTION:
XS GIS Cut Line= 6
     3178252.739    13961520.339     3179105.144    13961455.871
     3179448.785    13961205.017     3179579.402    13961018.221
     3179506.276    13960739.565     3179391.667    13960510.346
#Sta/Elev= 30
       0   65.58  216.83   63.62  252.45    61.3  322.17   60.89  414.07   63.13
  716.02   61.52  799.06    57.9  853.85    59.4  914.97   57.96 1055.86   58.85
 1092.36   47.86 1101.22   41.62 1104.25   41.37 1107.34   41.88 1115.59   47.49
 1142.28   53.35 1165.69   52.49 1176.72   48.55 1196.23   47.32  1281.9   54.33
 1509.83   57.48 1545.38   56.33 1569.58   51.18  1600.6   49.59 1631.62   54.34
 1658.57   55.58 1765.67   55.58 1961.37   61.79 2037.74   61.31  2054.2   62.61
#Mann= 3 ,-1 , 0
       0     .11       0 1055.86     .04       0 1142.28     .11       0
#Block Obstruct= 2 , 0
       0                    1500       0    57.5
Bank Sta=1055.86,1142.28
XS Rating Curve= 0
Exp/Cntr=.3,.1

Type RM Length L Ch R = 1 ,83.251  ,89.56,83.25,92.4
BEGIN DESCRIPTION:
adjust inv of 415v14
LOB block at watershed
END DESCRIPTION:
XS GIS Cut Line= 6
     3178391.908    13961900.115     3178882.359    13962095.428
     3179353.962    13961999.871     3179498.771    13961758.523
      3179614.92    13961013.361     3179390.172    13960476.504
#Sta/Elev= 30
       0   65.25   37.98   63.04  167.78   61.74   287.3   55.64  585.03   52.08
  788.51   58.93  986.33   58.54 1072.24   55.81  1076.9   54.74 1078.23   49.09
 1083.69   49.09 1122.24   38.85 1138.26   42.62 1143.21   46.54 1146.78   47.36
 1157.48   47.94 1171.34   43.32 1324.52    51.8 1520.89   59.26 1667.51    58.2
 1732.92   61.46 1789.25   59.52 1839.23   60.41 1899.83   58.77 2095.01   58.08
 2135.32   55.85 2324.44   55.68 2534.13   61.79  2615.9   61.22 2656.09   64.64
#Mann= 3 , 0 , 0
       0     .11       0 1083.69     .04       0 1146.78     .11       0
#Block Obstruct= 2 , 0
       0     835      60               0
Bank Sta=1083.69,1146.78
XS Rating Curve= 0
Exp/Cntr=.3,.1

Chan Stop Cuts=-1